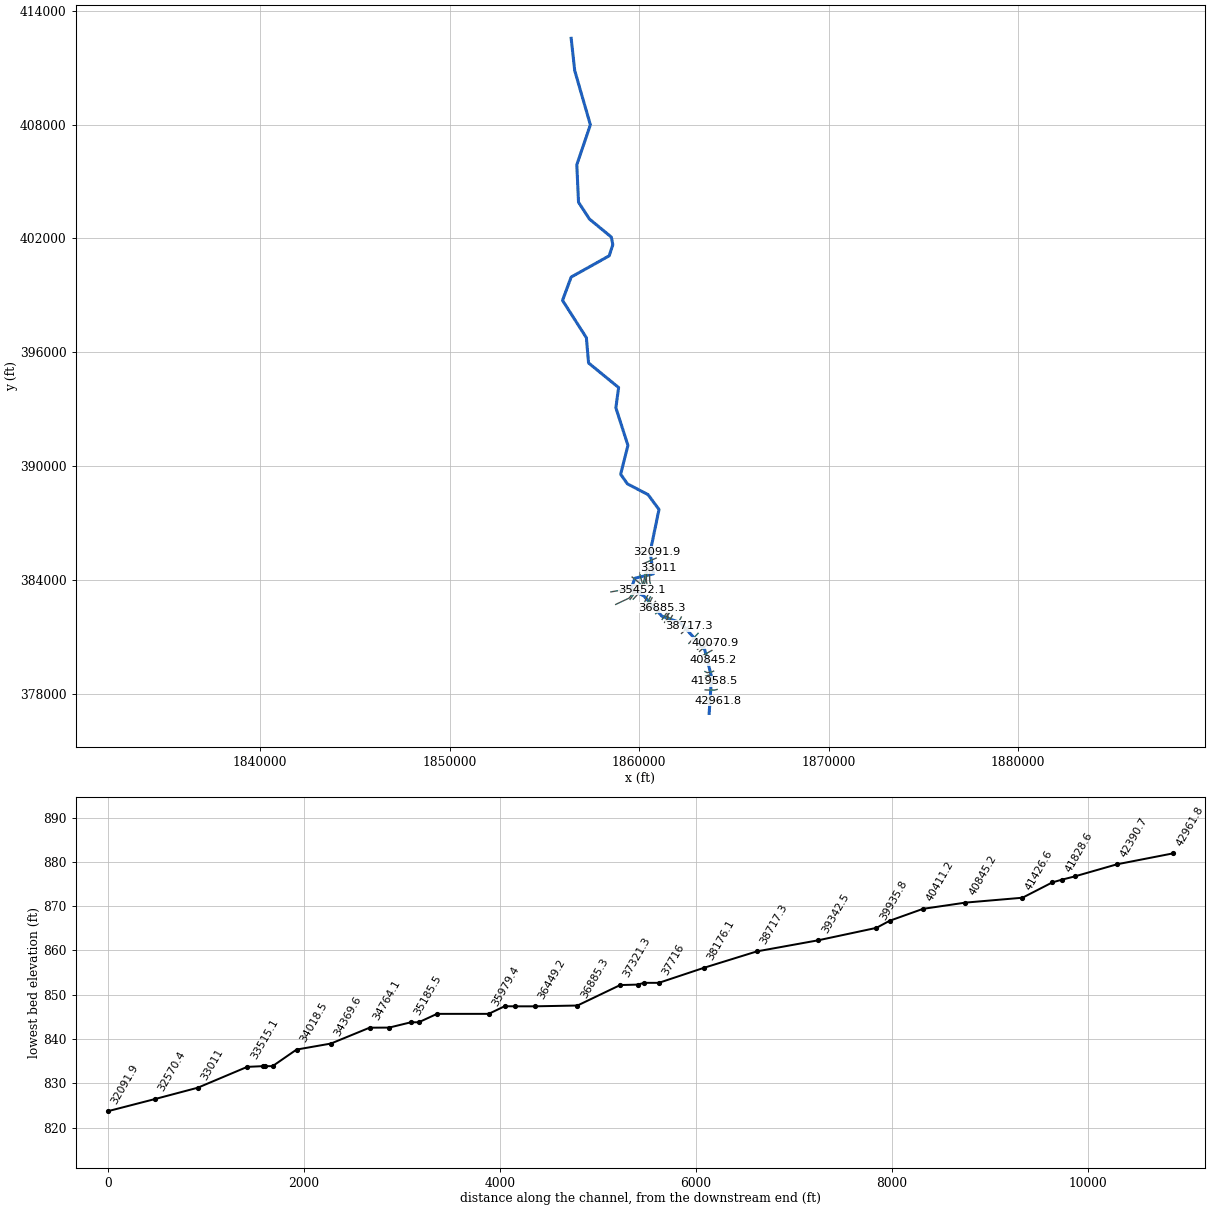
--- PAINTCK.prj (project) ---

Proj Title=PAINTCK
Current Plan=p01
Default Exp/Contr=0,0
English Units
Geom File=g01
Flow File=f01
Plan File=p01
BEGIN DESCRIPTION:
END DESCRIPTION:
DSS Export Rating Curves= 0
DSS Export Rating Curve Sorted= 0
DSS Export Volume Flow Curves= 0
DXF Filename=..\..\..\..\..\03_EngrWorking\AFG\PAINTCK\PAINTCK.
DXF OffsetX= 0
DXF OffsetY= 0
DXF ScaleX= 0
DXF ScaleY= 0

--- PAINTCK.p01 (plan) ---

Plan Title=Floodplain
Program Version=4.00
Geom File=g01
Flow File=f01
K Sum by GR=0
Std Step Tol=0.01
Critical Tol=0.01
Num of Std Step Trials=20
Max Error Tol=0.3
Flow Tol Ratio=0.001
Split Flow NTrial=30
Split Flow Tol=0.02
Split Flow Ratio=0.02
Log Output Level=0
Friction Slope Method=1
Unsteady Friction Slope Method=2
Unsteady Bridges Friction Slope Method=1
Global Log Level=0
CheckData=False
Run HTab=0
Run UNet=0
Run PostProcess=0
UNET Theta=0
UNET Theta Warmup=0
UNET ZTol=0
UNET ZSATol=0
UNET MxIter=0
UNET MaxInSteps=0
UNET DtIC=0
UNET DtMin=0
UNET MaxCRTS=0
UNET WFStab=0
UNET SFStab=0
UNET WFX=0
UNET SFX=0
UNET DSS MLevel=0
UNET DZMax Abort=0
UNET Convert EG Bridges=0
UNET Use Existing IB Tables=0
UNET Froude Limit=0
UNET Froude Power=0
Write IC File=0
Echo Input=False
Echo Output=False
Write Detailed=0

--- PAINTCK.f01 (steady flow) ---

Flow Title=NFF Regression Equation
Program Version=4.10
Number of Profiles= 1
Profile Names=P100yr
River Rch & RM=PAINTCK,Main            ,42961.8
11148.14
River Rch & RM=PAINTCK,Main            ,34764.1
 11879.8
River Rch & RM=PAINTCK,Main            ,12073.2
12729.12
River Rch & RM=PAINTCK,Main            ,572.4
13013.26
Boundary for River Rch & Prof#=PAINTCK,Main            , 1
Up Type= 0
Dn Type= 1
Dn Known WS=716.9
DSS Import GetInterval= 0
DSS Import GetPeak= 0
DSS Import FillOption= 0

--- PAINTCK.g01 (geometry) ---

Geom Title=USGS 10m DEM
Program Version=4.10

River Reach=PAINTCK         ,Main
Reach XY= 30
     1863688.875      376955.649     1863815.337      378878.769
     1863450.754      380326.685     1862155.615      381746.824
     1861197.282      382076.685     1860232.712      383155.302
     1859543.529      383491.327     1859777.904      384083.775
     1860745.786      384313.809     1860574.726      385456.445
     1861040.872      387709.049     1860460.143      388490.299
     1859370.577      389059.554     1859017.434       389565.82
     1859402.143       391083.63      1858764.83      393068.424
     1858910.663      394133.528     1857323.689      395432.086
     1857209.414      396760.207     1855949.421      398729.772
     1856406.757      399958.615      1858412.56      401080.158
     1858603.265      401667.717     1858526.876      402067.022
     1857370.626      403018.411     1856794.504      403903.074
     1856703.959      405879.522     1857419.504      407986.408
     1856593.115      410847.519     1856406.839      412545.783

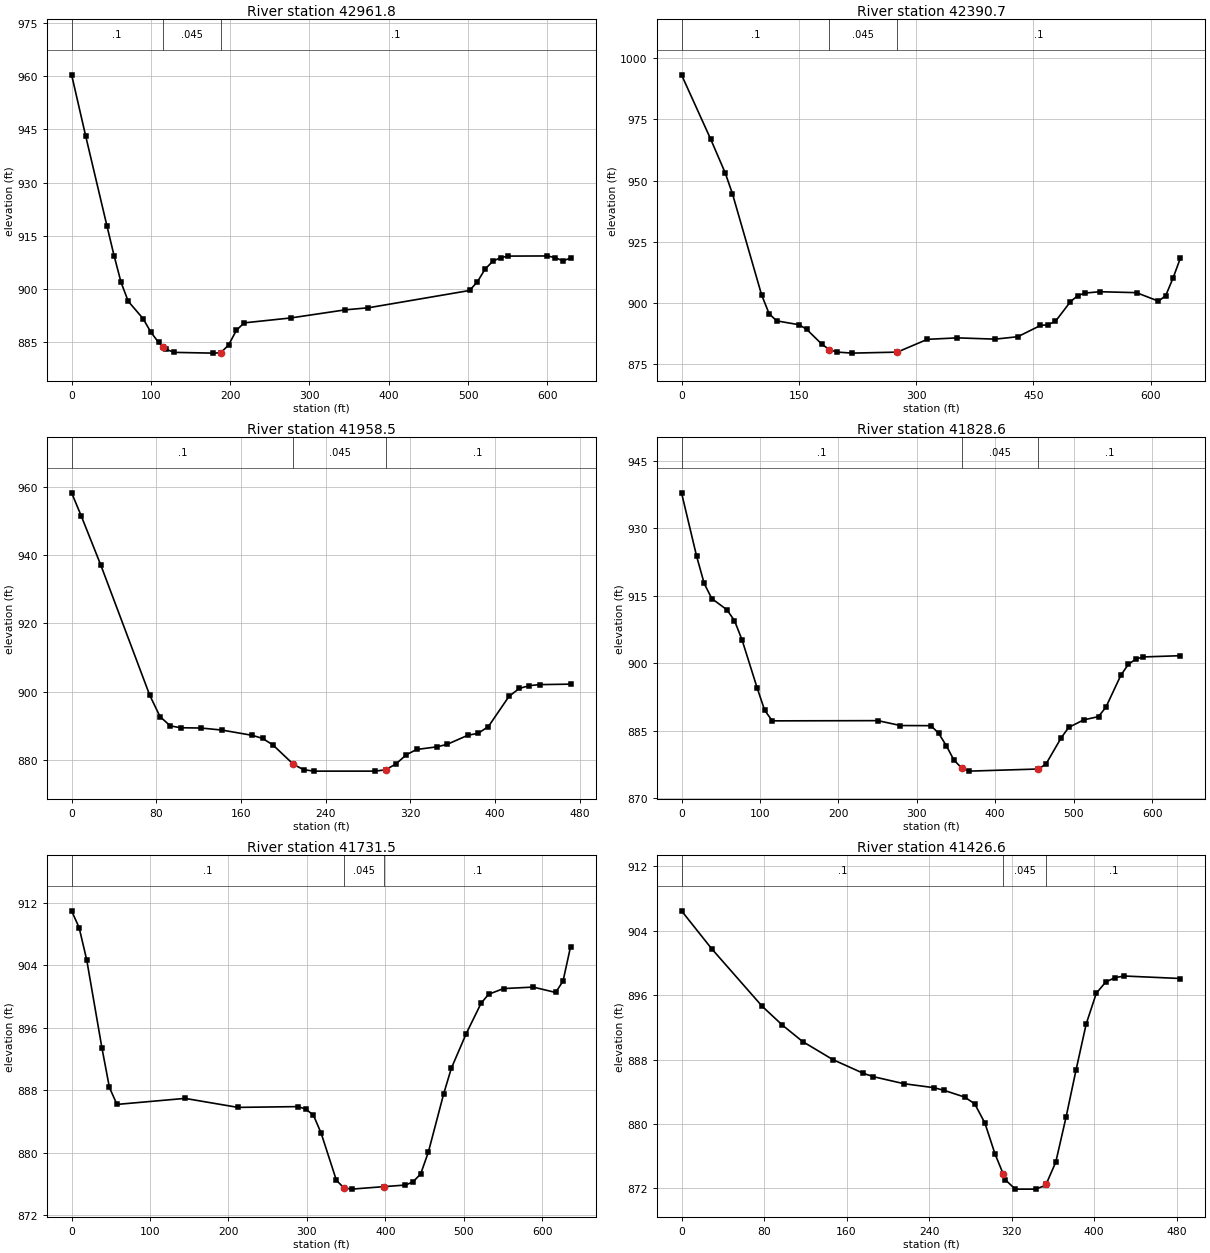
Type RM Length L Ch R = 1 ,42961.8 ,571.3,571.1,570.9
XS GIS Cut Line= 3
     1863532.273      377616.276     1863612.568      377616.276
     1864161.613      377618.446
#Sta/Elev= 30
       0  960.37    17.8  943.06    44.6  917.74    53.5  909.42    62.4  901.82
    71.4  896.52    90.1  891.64    99.9  887.83   109.7  884.92  115.07   883.7
   119.5  882.95   129.3  882.11   178.3   881.9   188.1     882     198   884.2
   207.8  888.32   217.6  890.43   276.4  891.82     345   894.1   374.4  894.69
   501.9  899.56   511.7  901.99   521.5  905.59   531.3  907.82   541.1  908.82
   550.9  909.26   599.9   909.3   609.7  908.85   619.5  907.92   629.3  908.69
#Mann= 3 , 0 , 0
       0      .1       0  115.07    .045       0   188.1      .1       0
Bank Sta=115.07,188.1
XS Rating Curve= 0 ,0
Exp/Cntr=0.3,0.1

Type RM Length L Ch R = 1 ,42390.7 ,429.3,432.2,435
XS GIS Cut Line= 4
      1863478.02      378195.703     1863580.016      378187.023
     1863974.982      378184.852       1864111.7      378217.405
#Sta/Elev= 30
       0  993.26    37.2  967.01    55.8   953.2    65.1  944.63   102.4  903.24
     112  895.56   121.6  892.64   150.5  891.04   160.2  889.12   179.4  883.09
   189.1  880.84   198.7  879.88     218  879.44   275.8  879.85   314.3  885.08
   352.8  885.68     401  885.16   429.9  886.15   458.8  890.74   468.4  891.07
   478.1  892.46   497.3  900.49   506.7     903   516.1  904.01   534.8  904.55
   581.7  904.17   609.8  900.69   619.1  902.99   628.5  910.22   637.9   918.4
#Mann= 3 , 0 , 0
       0      .1       0   189.1    .045       0   275.8      .1       0
Bank Sta=189.1,275.8
XS Rating Curve= 0 ,0
Exp/Cntr=0.3,0.1

Type RM Length L Ch R = 1 ,41958.5 ,153.5,129.9,105.3
XS GIS Cut Line= 3
     1863506.232      378595.009     1863580.016      378595.009
     1863974.982      378640.582
#Sta/Elev= 30
       0  958.22     9.2  951.37    27.7  936.95    73.8  898.94    83.5  892.68
    93.2  889.96   102.9  889.41   122.3  889.32   141.7  888.74   170.8  887.18
   180.4  886.29   190.2  884.37   209.6  878.68   219.2  877.12   228.9   876.7
   287.1   876.7   296.8   877.1   306.5  878.83   316.2  881.48   325.9  883.04
   345.3  883.82     355  884.57   374.4  887.21   384.1  887.78   393.8  889.77
   413.2  898.58   422.9  900.92   432.6  901.75   442.3  902.04   471.4  902.18
#Mann= 3 , 0 , 0
       0      .1       0   209.6    .045       0   296.8      .1       0
Bank Sta=209.6,296.8
XS Rating Curve= 0 ,0
Exp/Cntr=0.3,0.1

Type RM Length L Ch R = 1 ,41828.6 ,97.1,97.1,98.1
XS GIS Cut Line= 5
     1863462.829      378831.554     1863664.652      378896.658
     1863701.544      378829.384     1863829.582      378681.814
     1863979.322      378707.856
#Sta/Elev= 30
       0  937.93    19.3  923.78    28.9  917.76    38.6  914.38    57.8  911.91
    67.5  909.49    77.1  905.23    96.4  894.51     106  889.53   115.7  887.16
   250.4  887.21   279.2  886.12   318.1  886.09   327.9  884.38   337.6  881.64
   347.4  878.41   357.2  876.68   366.9  875.97   454.9  876.44   464.6  877.51
   484.2  883.41   493.7   885.7   512.7  887.37   531.7  888.11   541.2  890.23
   560.2  897.32   569.7  899.73   579.2  900.91   588.6  901.39   636.2  901.67
#Mann= 3 , 0 , 0
       0      .1       0   357.2    .045       0   454.9      .1       0
Bank Sta=357.2,454.9
XS Rating Curve= 0 ,0
Exp/Cntr=0.3,0.1

Type RM Length L Ch R = 1 ,41731.5 ,280.1,304.8,329.6
XS GIS Cut Line= 5
     1863497.551      378916.189     1863699.374      378981.293
     1863736.266      378914.019     1863864.304       378766.45
     1864014.044      378792.491
#Sta/Elev= 30
       0  910.94     9.6  908.78    19.3  904.65    38.6  893.44    48.2  888.36
    57.8  886.19   144.6  886.96   212.1  885.81   288.8  885.91   298.6  885.59
   308.3  884.82   318.1  882.53   337.6  876.49   347.4   875.5   357.2  875.36
   398.3  875.68   425.6  875.88   435.3  876.28   445.1  877.31   454.9   880.1
   474.4  887.54   484.2  890.82   503.2  895.25   522.2  899.14   531.7  900.27
   550.7     901   588.6  901.19   617.2   900.5   626.6  901.96   636.2  906.36
#Mann= 3 , 0 , 0
       0      .1       0   347.4    .045       0   398.3      .1       0
Bank Sta=347.4,398.3
XS Rating Curve= 0 ,0
Exp/Cntr=0.3,0.1

Type RM Length L Ch R = 1 ,41426.6 ,578.7,581.4,584.1
XS GIS Cut Line= 4
     1863464.999      379161.415     1863577.846      379102.821
     1863849.113      379148.394     1863922.898      379183.116
#Sta/Elev= 30
       0  906.48    29.3  901.76    78.2  894.62    97.8  892.28   117.4  890.24
   146.8  887.99   176.3  886.29   186.1  885.87   215.6     885     245   884.5
   254.9  884.16   274.5  883.34   284.3   882.5   294.2   880.1     304  876.26
  311.78  873.83   313.8  873.08   323.6   871.9   343.3   871.9   353.1  872.37
   353.8  872.58   362.9  875.26   372.8  880.81   382.6  886.74   392.4  892.43
   402.2  896.24   411.3  897.63   420.3  898.18   429.4  898.38   483.8  898.07
#Mann= 3 , 0 , 0
       0      .1       0  311.78    .045       0   353.8      .1       0
Bank Sta=311.78,353.8
XS Rating Curve= 0 ,0
Exp/Cntr=0.3,0.1

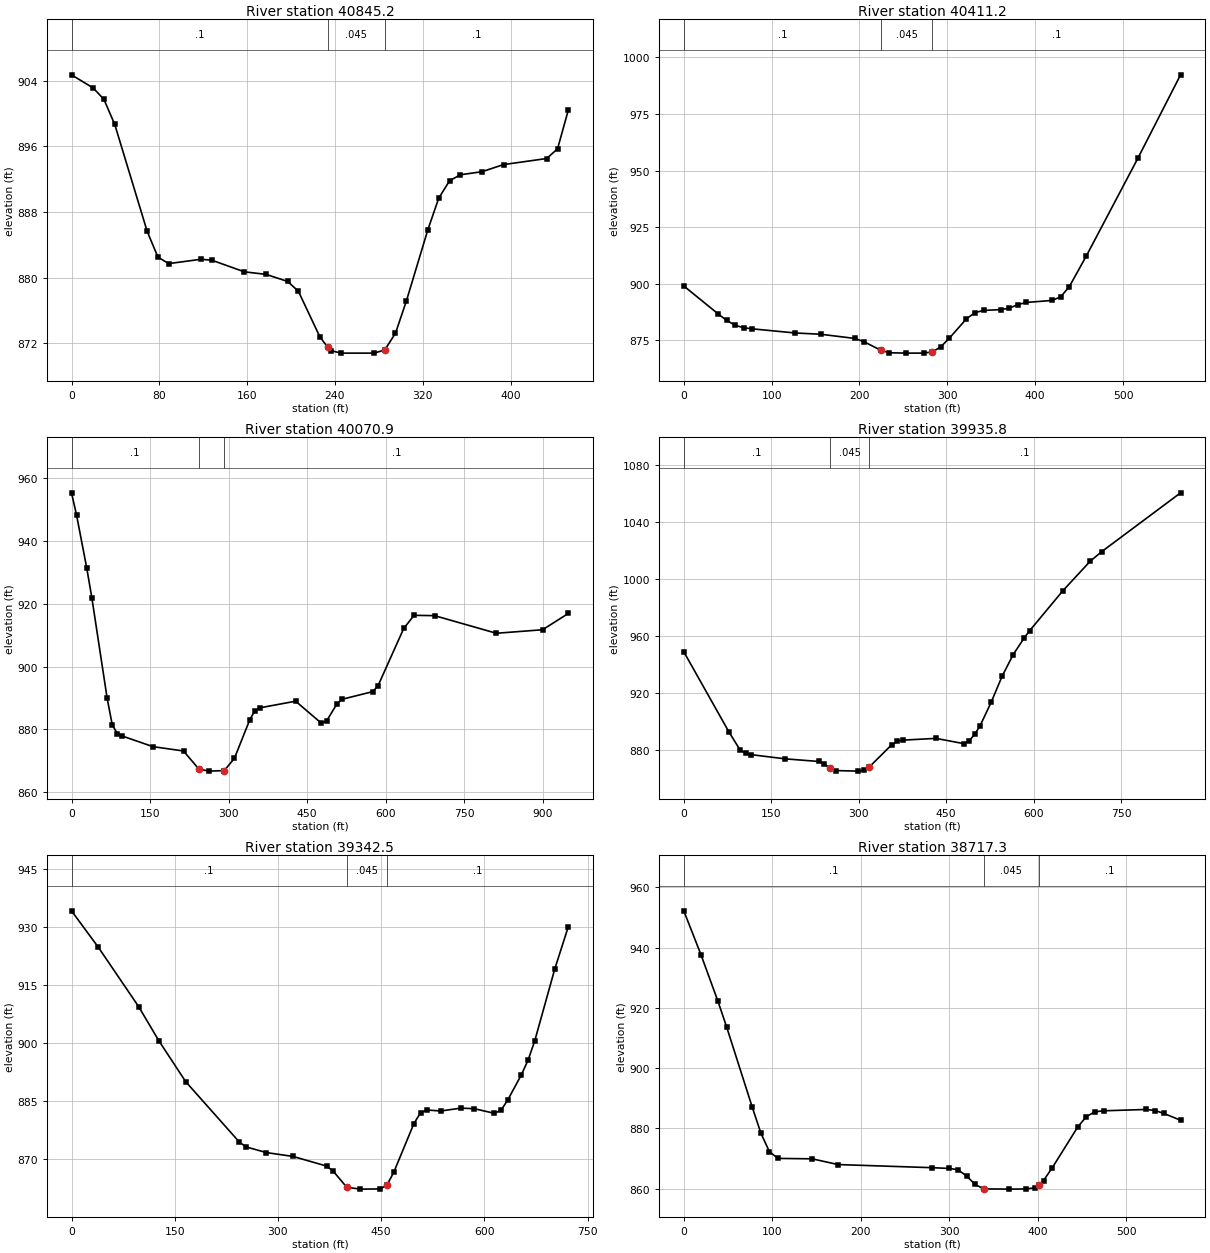
Type RM Length L Ch R = 1 ,40845.2 ,428.9,434,439.2
XS GIS Cut Line= 2
     1863438.957      379636.675     1863872.985      379764.714
#Sta/Elev= 30
       0  904.72    19.7  903.12    29.5  901.74    39.4  898.67    68.9  885.65
    78.7  882.51    88.5  881.71     118  882.24   127.9  882.12   157.4  880.71
   177.1   880.4   196.8  879.54   206.6  878.35   226.3  872.76  233.39  871.52
   236.1   871.1   245.9   870.8   275.4   870.8   285.3  871.18   295.1  873.23
     305  877.15   324.6  885.85   334.5  889.69   344.3   891.8   354.2  892.54
   373.8  892.91   393.5  893.78   432.8  894.52   442.7   895.7   452.5  900.42
#Mann= 3 , 0 , 0
       0      .1       0  233.39    .045       0   285.3      .1       0
Bank Sta=233.39,285.3
XS Rating Curve= 0 ,0
Exp/Cntr=0.3,0.1

Type RM Length L Ch R = 1 ,40411.2 ,334.9,340.3,345.8
XS GIS Cut Line= 2
     1863339.131      379996.918     1863831.752      380274.696
#Sta/Elev= 30
       0  899.04      39  886.74    48.8  883.84    58.5  881.68    68.2   880.6
      78  880.11   126.8  878.29     156  877.72     195  875.86   204.8  874.48
   224.3  870.66     234  869.55   253.5  869.39     273   869.4   282.8  869.92
   292.5  872.15   302.3  875.99   321.8  884.56   331.5  887.27   341.3  888.24
   360.8   888.6   370.5  889.24   380.3  890.82     390  891.77   419.3  892.66
     429  894.24   438.8  898.71   458.3  912.34   516.8  955.36   565.5  992.26
#Mann= 3 , 0 , 0
       0      .1       0   224.3    .045       0   282.8      .1       0
Bank Sta=224.3,282.8
XS Rating Curve= 0 ,0
Exp/Cntr=0.3,0.1

Type RM Length L Ch R = 1 ,40070.9 ,136.4,135,133.7
XS GIS Cut Line= 4
     1863180.711      380220.443      1863478.02      380500.391
     1863692.863      380598.047     1863990.172      380663.151
#Sta/Elev= 30
       0   955.4     9.7  948.26    29.2  931.34    38.9  921.89    68.1  889.88
    77.8  881.45    87.5  878.69    97.2  877.87   155.6   874.5   213.9  873.12
   243.1  867.37   262.5   866.7   291.7  866.87   311.1  870.78   340.3  883.01
     350  885.92   359.8  886.88     428  888.99   477.2  881.97     487  882.66
   506.7  888.07   516.5  889.59   575.5  892.05   585.4  893.93   634.5   912.2
   654.2  916.36   693.4  916.25   811.3  910.64   899.6  911.76   948.7  916.95
#Mann= 3 , 0 , 0
       0      .1       0   243.1    .045       0   291.7      .1       0
Bank Sta=243.1,291.7
XS Rating Curve= 0 ,0
Exp/Cntr=0.3,0.1

Type RM Length L Ch R = 1 ,39935.8 ,590.2,593.3,596.3
XS GIS Cut Line= 5
     1863074.374       380328.95     1863363.002      380569.835
     1863464.999       380654.47     1863560.485      380817.231
     1863666.822      380930.078
#Sta/Elev= 30
       0   948.8    77.1  892.82    96.4  880.02     106  877.46   115.7  876.64
   173.5  873.73   231.4  871.87     241  870.05   250.6     867   260.3  865.49
   298.8   865.1   308.5  865.75   318.1  867.97   356.7  883.58   366.3  885.97
   375.9  886.83   432.7  888.06   480.1  884.38   489.6   886.4     499  890.82
   508.5  897.08   527.4  913.52   546.2  931.75   565.1  946.81     584  958.54
   593.4   963.6     650  991.44   697.2 1012.26   716.6 1018.88   852.2 1060.21
#Mann= 3 , 0 , 0
       0      .1       0   250.6    .045       0   318.1      .1       0
Bank Sta=250.6,318.1
XS Rating Curve= 0 ,0
Exp/Cntr=0.3,0.1

Type RM Length L Ch R = 1 ,39342.5 ,626.5,625.2,624.1
XS GIS Cut Line= 2
     1862616.475       380643.62     1863102.586      381177.474
#Sta/Elev= 30
       0  934.27      39  924.84    97.6  909.49   126.8  900.71   165.9   890.1
   243.9  874.48   253.7  873.22     283  871.76     322  870.75   370.8  868.26
   380.5  866.91     400  862.79   419.4   862.3   448.8  862.35   458.6  863.41
   468.3  866.63   497.6  879.25   507.4  882.09   517.1  882.76   536.6   882.5
   565.9  883.25   585.4   883.1   614.7   881.9   624.4  882.74   634.2  885.41
   653.7  891.84   663.5  895.63   673.2  900.63   702.5  919.33     722  930.17
#Mann= 3 , 0 , 0
       0      .1       0     400    .045       0   458.6      .1       0
Bank Sta=400,458.6
XS Rating Curve= 0 ,0
Exp/Cntr=0.3,0.1

Type RM Length L Ch R = 1 ,38717.3 ,534.3,541.2,548.1
XS GIS Cut Line= 2
      1862228.02      381168.793     1862627.325      381563.759
#Sta/Elev= 30
       0  952.22    19.4  937.68    38.7  922.12    48.4  913.69    77.5  886.92
    87.2  878.36    96.8  872.23   106.5     870   145.2  869.86   174.3  867.96
   280.8  866.92   300.2  866.67   309.9  866.25   319.6  864.19   329.2  861.39
   338.9  859.88     368   859.8   387.3  859.86     397  860.25  401.77  861.12
   406.7  862.66   416.4  866.83   445.4  880.45   455.1  883.89   464.8  885.48
   474.5  885.81   522.9  886.26   532.6  885.91   542.3  884.98   561.6  882.68
#Mann= 3 , 0 , 0
       0      .1       0   338.9    .045       0  401.77      .1       0
Bank Sta=338.9,401.77
XS Rating Curve= 0 ,0
Exp/Cntr=0.3,0.1

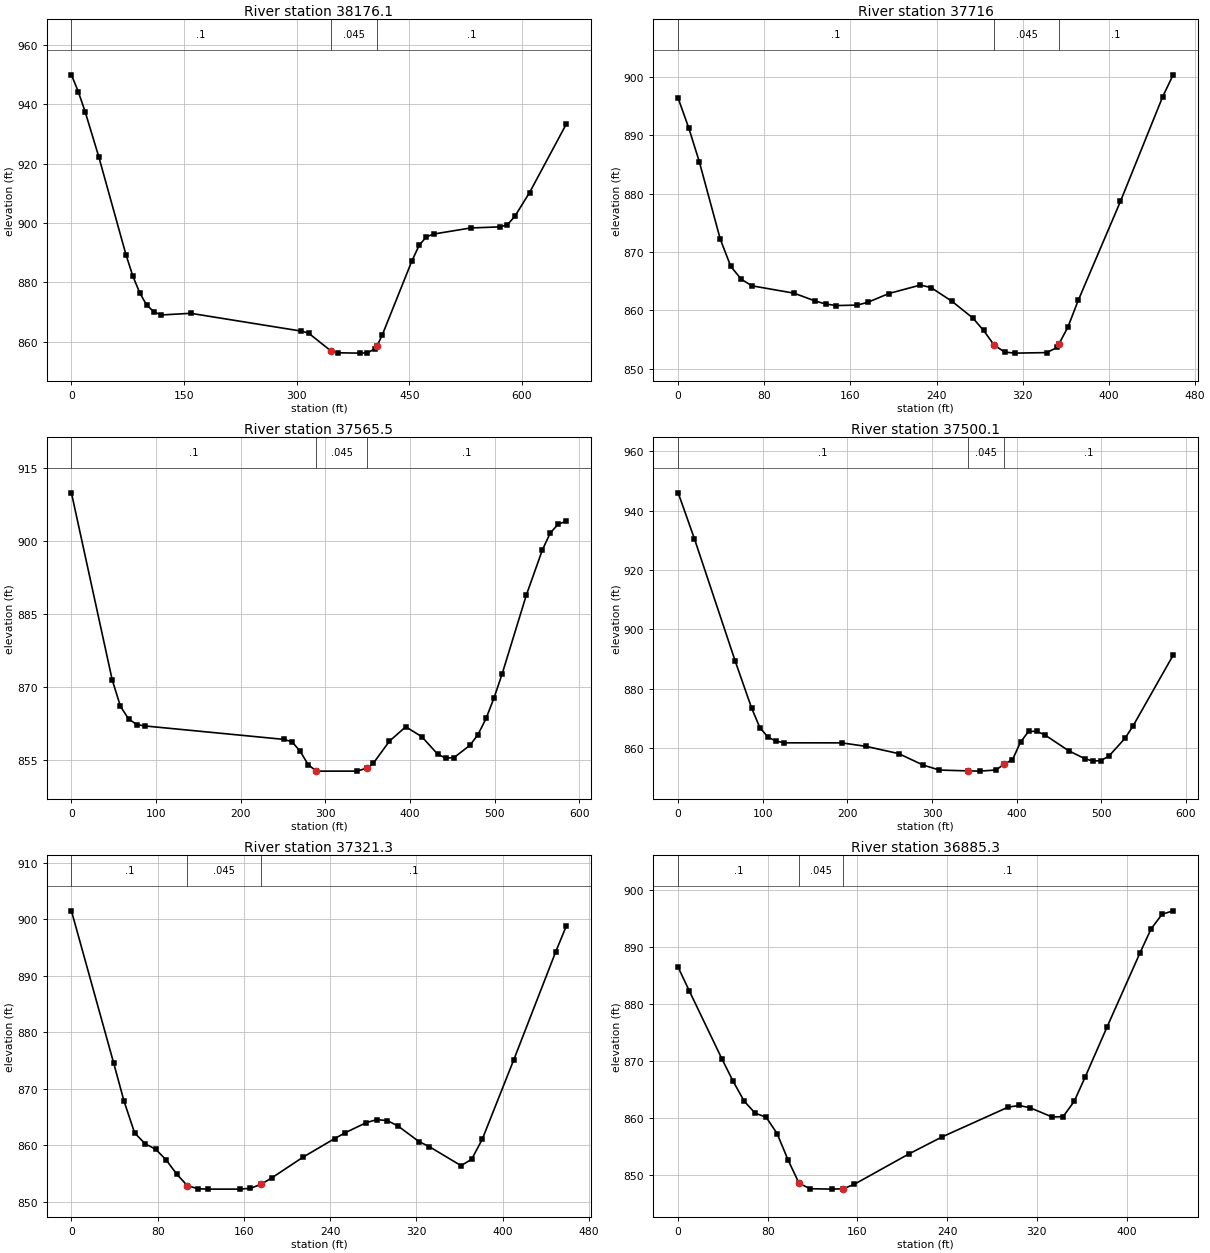
Type RM Length L Ch R = 1 ,38176.1 ,460.3,460.1,459.9
XS GIS Cut Line= 3
      1861913.35      381453.082     1861958.922      381542.057
     1862219.339      382036.849
#Sta/Elev= 30
       0  949.95     9.1  944.31    18.2  937.58    36.4  922.34    72.7  889.24
    81.8  882.06    90.9  876.48     100  872.37   109.8  870.01   119.6  868.96
   158.8  869.52     306  863.52   315.8  862.84   345.2  856.91     355   856.2
     384  856.09   394.2  856.19   404.1  857.54  406.73  858.37   413.9  862.19
   453.1  887.01   462.9   892.4   472.7  895.32   482.5  896.26   531.6   898.3
   570.8  898.67   580.6  899.41   590.4   902.2   610.1  910.26   659.1   933.4
#Mann= 3 , 0 , 0
       0      .1       0   345.2    .045       0  406.73      .1       0
Bank Sta=345.2,406.73
XS Rating Curve= 0 ,0
Exp/Cntr=0.3,0.1

Type RM Length L Ch R = 1 ,37716   ,122.8,150.5,185.7
XS GIS Cut Line= 2
     1861525.763      381709.158     1861743.211      382114.106
#Sta/Elev= 30
       0  896.33     9.8  891.25    19.6  885.48    39.1   872.2    48.9  867.53
    58.7  865.33    68.5  864.22   107.6  862.96   127.1  861.63   136.9  861.11
   146.7  860.84   166.2  860.92     176  861.39   195.6   862.9   224.9  864.35
   234.7  863.93   254.3  861.56   273.8  858.68   283.6  856.58   293.4  854.08
   303.2  852.88   312.9   852.7   342.3  852.79   352.1   853.7  353.41  854.21
   361.8  857.12   371.6  861.78   410.7  878.68   449.9  896.58   459.6  900.33
#Mann= 3 , 0 , 0
       0      .1       0   293.4    .045       0  353.41      .1       0
Bank Sta=293.4,353.41
XS Rating Curve= 0 ,0
Exp/Cntr=0.3,0.1

Type RM Length L Ch R = 1 ,37565.5 ,59.3,65.4,63.4
XS GIS Cut Line= 4
     1861383.836      381771.658     1861555.711       382016.45
     1861484.096      382080.252     1861581.752      382243.012
#Sta/Elev= 30
       0  909.86    48.2  871.44    57.9  866.02    67.5  863.43    77.2  862.26
    86.8  861.98   250.9  859.22   260.5  858.74   270.2  856.81   279.8     854
   289.5   852.7   337.5   852.7  349.69  853.37   356.6  854.29   375.8  858.87
     395  861.81     414  859.77     433  856.13   442.5  855.38     452  855.48
   470.9  858.01   480.4  860.22   489.9  863.51   499.4  867.78   508.9  872.67
   537.4  888.81   556.4  898.12   565.8  901.63   575.3  903.45   584.8  904.01
#Mann= 3 , 0 , 0
       0      .1       0   289.5    .045       0  349.69      .1       0
Bank Sta=289.5,349.69
XS Rating Curve= 0 ,0
Exp/Cntr=0.3,0.1

Type RM Length L Ch R = 1 ,37500.1 ,215.7,178.8,142.4
XS GIS Cut Line= 4
     1861336.961      381750.825     1861508.836      381995.616
     1861437.221      382059.418     1861534.877      382222.179
#Sta/Elev= 30
       0  946.02    19.3  930.48    67.5  889.27    86.8  873.53    96.5  866.96
   106.1  863.75   115.8  862.39   125.4  861.83     193  861.82   221.9  860.65
   260.5   858.2   289.5  854.33   308.7  852.66   342.3  852.38   356.6   852.3
   375.8  852.69   385.4  854.75     395  856.13   404.5  862.09     414  865.66
   423.5  865.72     433  864.54   461.4  859.16   480.4   856.5   489.9  855.69
   499.4  855.84   508.9  857.36   527.9  863.34   537.4   867.5   584.8  891.33
#Mann= 3 , 0 , 0
       0      .1       0   342.3    .045       0   385.4      .1       0
Bank Sta=342.3,385.4
XS Rating Curve= 0 ,0
Exp/Cntr=0.3,0.1

Type RM Length L Ch R = 1 ,37321.3 ,439.3,436,432.7
XS GIS Cut Line= 2
     1861209.357      381909.679     1861472.377      382285.981
#Sta/Elev= 30
       0   901.5    39.1   874.6    48.8  867.78    58.6  862.17    68.4  860.22
    78.2  859.27    87.9  857.36    97.7  854.86   107.4  852.84   117.2  852.27
     127   852.2   156.3   852.2   166.1  852.35   175.8  853.05   185.6  854.16
   214.9  857.87   244.2  861.16     254  862.19   273.5  863.98   283.3  864.51
     293  864.34   302.8   863.4   322.4  860.62   332.1  859.71   361.4  856.36
   371.2  857.49     381     861   410.3  875.11   449.3  894.29   459.1  898.84
#Mann= 3 , 0 , 0
       0      .1       0   107.4    .045       0   175.8      .1       0
Bank Sta=107.4,175.8
XS Rating Curve= 0 ,0
Exp/Cntr=0.3,0.1

Type RM Length L Ch R = 1 ,36885.3 ,433.4,436.1,438.5
XS GIS Cut Line= 2
     1860867.777      382207.856     1861177.933      382522.179
#Sta/Elev= 28
       0  886.43     9.8  882.35    39.2  870.32    49.1  866.44    58.9  862.99
    68.7  860.88    78.5  860.18    88.3   857.3    98.1  852.66   107.9  848.59
   117.8  847.65   137.4  847.58   147.2  847.64     157  848.41   206.1  853.77
   235.5  856.73   294.4  861.94   304.2  862.23     314  861.83   333.6  860.22
   343.4  860.27   353.3  862.94   363.1   867.2   382.7     876   412.1  888.98
     422  893.18   431.8  895.73   441.6  896.32
#Mann= 3 , 0 , 0
       0      .1       0   107.9    .045       0   147.2      .1       0
Bank Sta=107.9,147.2
XS Rating Curve= 0 ,0
Exp/Cntr=0.3,0.1

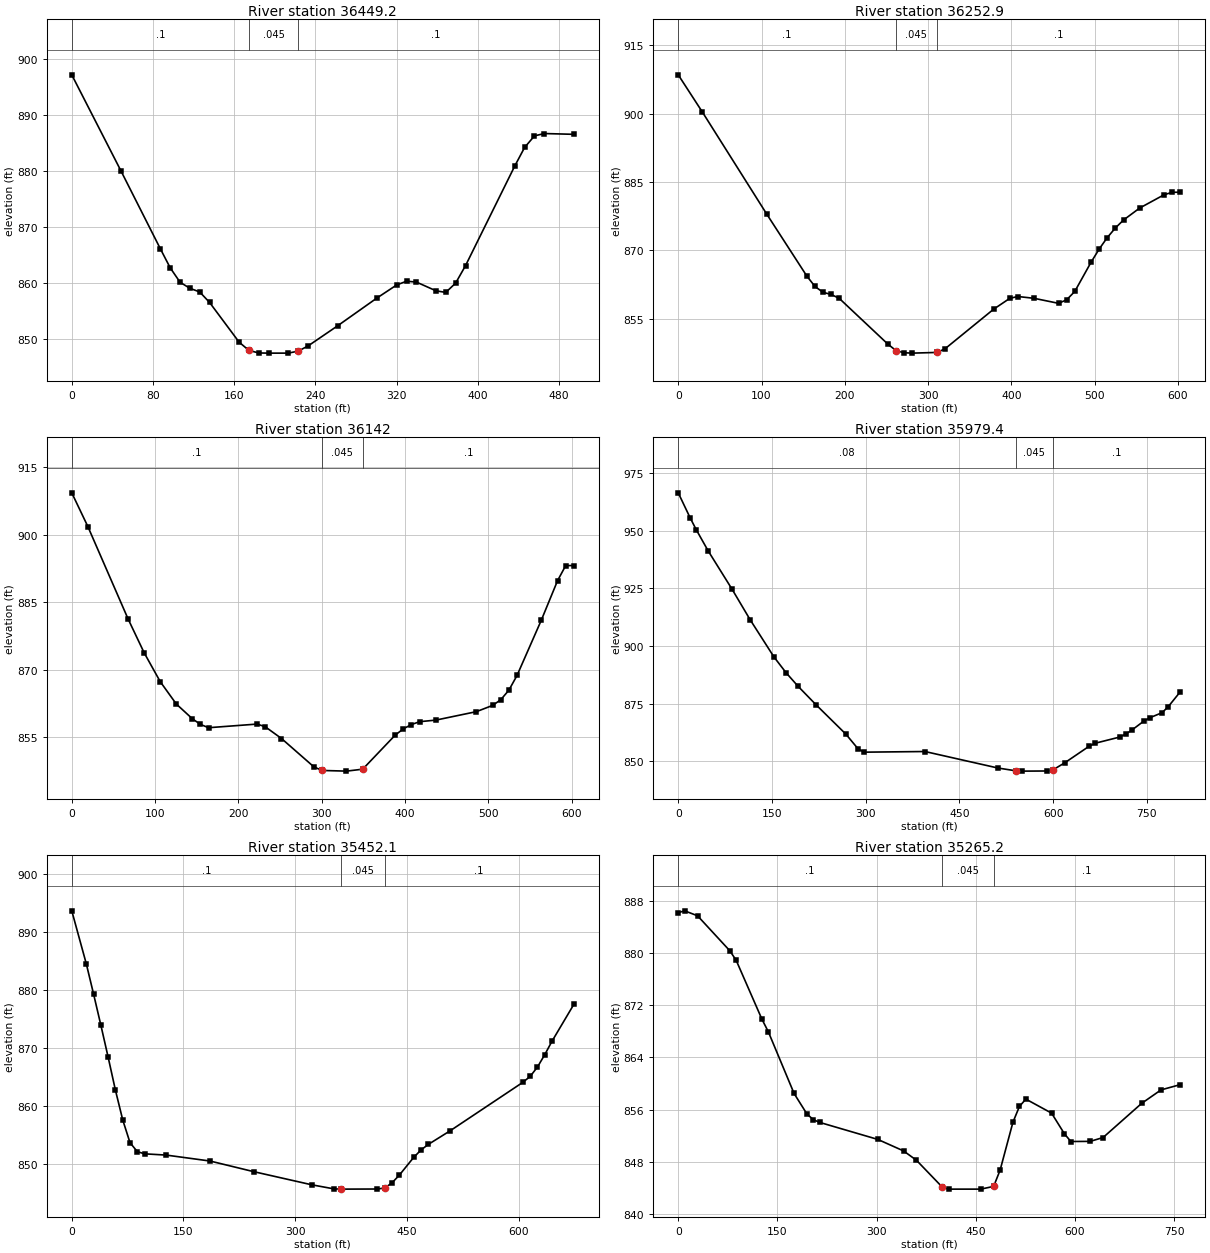
Type RM Length L Ch R = 1 ,36449.2 ,191.4,196.3,201.2
XS GIS Cut Line= 2
     1860546.857      382469.372     1860852.846      382857.827
#Sta/Elev= 29
       0  897.17    48.5  879.97    87.3  866.04      97  862.64   106.7  860.07
   116.4  858.99     126  858.34   135.7  856.47   164.8  849.37   174.5  847.88
   184.2  847.43   193.9   847.4   213.3   847.4     223  847.76   232.7  848.68
   261.8  852.28   300.6  857.26     320  859.59   329.7  860.26   339.4  860.11
   358.8  858.54   368.4  858.26   378.1  859.93   387.8  863.04   436.3  880.86
     446  884.18   455.7  886.25   465.4  886.67   494.5  886.53
#Mann= 3 , 0 , 0
       0      .1       0   174.5    .045       0     223      .1       0
Bank Sta=174.5,223
XS Rating Curve= 0 ,0
Exp/Cntr=0.3,0.1

Type RM Length L Ch R = 1 ,36252.9 ,111,110.9,111.2
XS GIS Cut Line= 3
     1860475.242      382491.073     1860483.922      382664.685
     1860674.895      383048.799
#Sta/Elev= 30
       0  908.54      29  900.36   106.2  877.96   154.5   864.3   164.2  862.04
   173.8  860.76   183.6  860.29   193.3  859.43   251.8  849.36   261.6  847.94
   271.3  847.48   281.1   847.4   310.3  847.55   320.1  848.32   378.6  857.04
   398.1  859.44   407.8  859.84   427.3  859.44   456.6  858.34   466.3  859.11
   476.1  860.95   495.6  867.36   505.3  870.24     515  872.76   524.8  874.89
   534.6  876.64     554  879.27   583.3  882.19     593  882.73   602.8  882.76
#Mann= 3 , 0 , 0
       0      .1       0   261.6    .045       0   310.3      .1       0
Bank Sta=261.6,310.3
XS Rating Curve= 0 ,0
Exp/Cntr=0.3,0.1

Type RM Length L Ch R = 1 ,36142   ,161.1,162.6,164.3
XS GIS Cut Line= 3
     1860384.096      382543.157     1860392.777      382716.768
     1860583.749      383100.883
#Sta/Elev= 30
       0  909.28    19.3  901.79    67.6  881.25    86.9  873.73   106.2  867.31
   125.5  862.34   144.9  859.04   154.5  857.81   164.2  857.07   222.6  857.88
   232.3  857.28   251.8  854.67   290.8  848.35   300.6  847.57   329.8  847.42
   349.3  847.85   388.3  855.42   398.1  856.82   407.8  857.77   417.6  858.41
   437.1  858.76   485.8  860.64   505.3  862.03     515  863.28   524.8  865.41
   534.6  868.69   563.8     881   583.3  889.78     593   893.1   602.8  893.12
#Mann= 3 , 0 , 0
       0      .1       0   300.6    .045       0   349.3      .1       0
Bank Sta=300.6,349.3
XS Rating Curve= 0 ,0
Exp/Cntr=0.3,0.1

Type RM Length L Ch R = 1 ,35979.4 ,535.6,527.4,518.9
XS GIS Cut Line= 3
     1860036.125      382511.644     1860227.846      382699.407
      1860447.03      383187.688
#Sta/Elev= 30
       0  966.36    19.2  955.44    28.8  950.38    47.9  941.19    86.3   924.5
     115  911.38   153.3  895.17   172.5   888.4   191.7  882.51   220.4  874.51
   268.4  861.71   287.8  855.37   297.5  853.92   394.9   854.2   511.6  847.05
   540.8  845.82   550.6   845.7   589.5  845.76   599.2  846.16   618.7  849.32
   657.6  856.48   667.3  857.79   706.3  860.45     716  861.73   725.7  863.42
   745.2  867.39   754.9  868.85   774.4  871.04   784.1  873.59   803.6  880.12
#Mann= 3 , 0 , 0
       0     .08       0   540.8    .045       0   599.2      .1       0
Bank Sta=540.8,599.2
XS Rating Curve= 0 ,0
Exp/Cntr=0.3,0.1

Type RM Length L Ch R = 1 ,35452.1 ,184.2,186.8,189.4
XS GIS Cut Line= 2
     1859680.971      382977.185       1860136.7      383474.146
#Sta/Elev= 30
       0  893.63    19.5  884.51    29.3  879.29    39.1  873.92    48.9   868.4
    58.6  862.76    68.4  857.64    78.2   853.7      88  852.16    97.7  851.78
     127  851.56   185.7  850.54   244.3  848.71   322.5  846.44   351.8  845.75
   361.6   845.7   410.4  845.72   420.2  845.89     430  846.77   439.8  848.09
   459.3  851.18   469.1  852.45   478.8   853.4   508.2  855.75   605.9   864.1
   615.6  865.11   625.4  866.72   635.2  868.85     645  871.18   674.3  877.52
#Mann= 3 , 0 , 0
       0      .1       0   361.6    .045       0   420.2      .1       0
Bank Sta=361.6,420.2
XS Rating Curve= 0 ,0
Exp/Cntr=0.3,0.1

Type RM Length L Ch R = 1 ,35265.2 ,79.4,79.7,80
XS GIS Cut Line= 2
     1859517.487      382966.153     1859958.026      383584.643
#Sta/Elev= 30
       0  886.18     9.7  886.46    29.2   885.7    77.9  880.35    87.6  878.88
   126.6  869.84   136.3  867.91   175.2  858.46   194.7  855.31   204.4  854.44
   214.2  854.02   301.8  851.42   340.7  849.66   360.2  848.23   399.1  844.13
   408.9   843.8   457.6   843.8     477  844.22   486.8  846.72   506.2  854.06
     516  856.48   525.7   857.6   564.6  855.45   584.1  852.27   593.8   851.1
     623  851.12   642.5  851.71   700.9  856.95   730.1  859.01   759.3  859.82
#Mann= 3 , 0 , 0
       0      .1       0   399.1    .045       0     477      .1       0
Bank Sta=399.1,477
XS Rating Curve= 0 ,0
Exp/Cntr=0.3,0.1

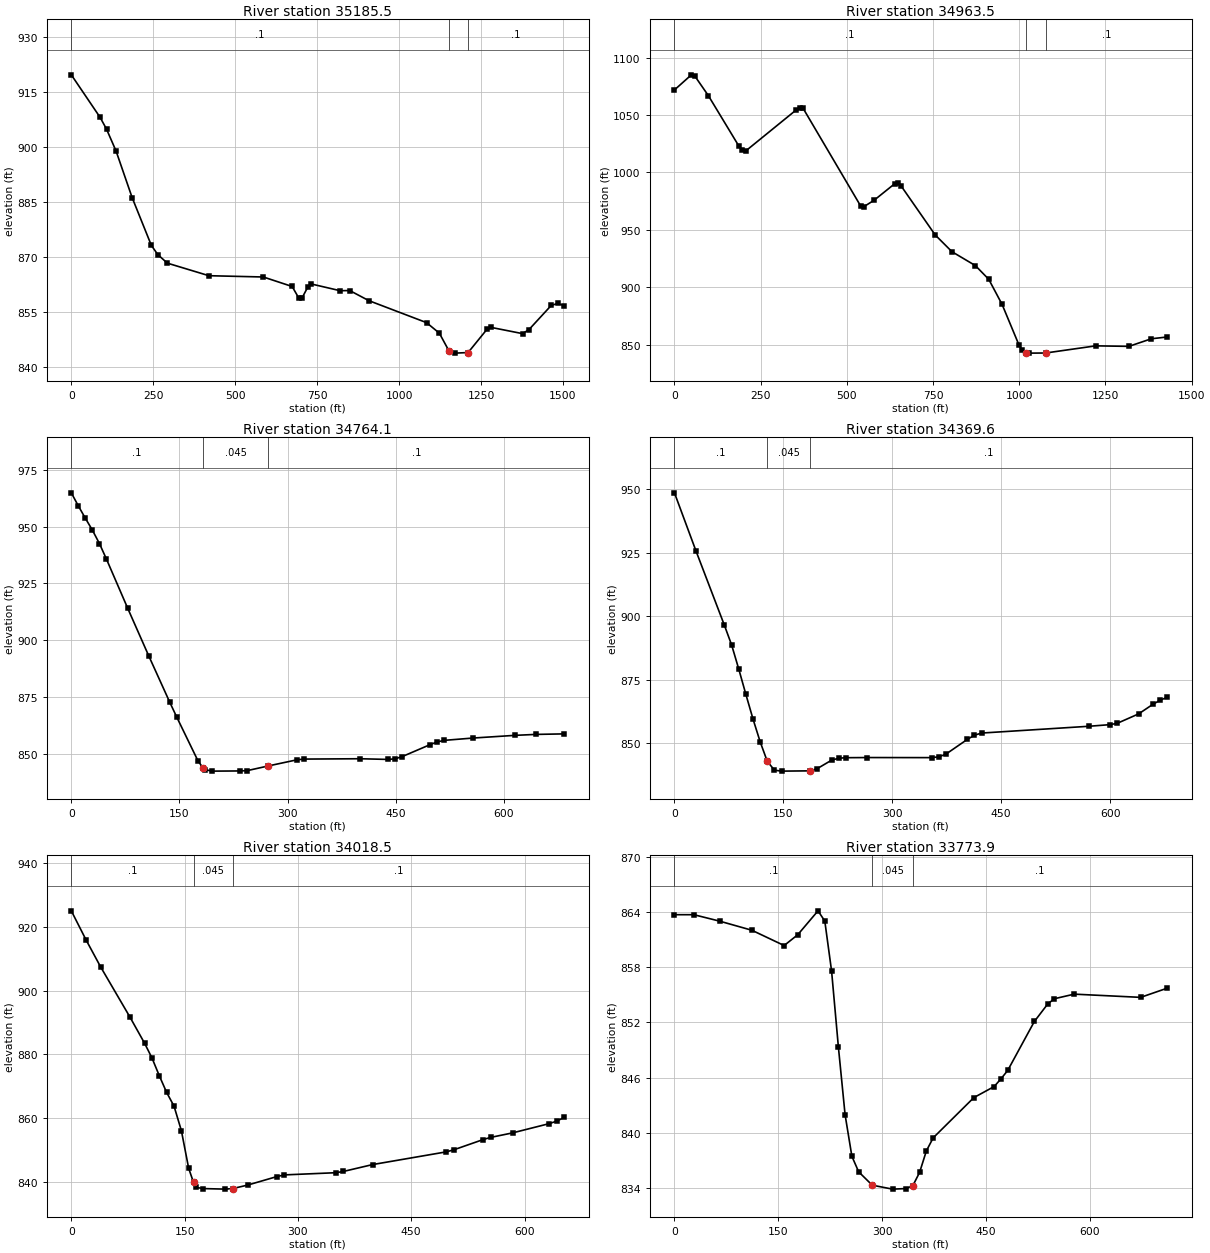
Type RM Length L Ch R = 1 ,35185.5 ,242.1,222,201.7
XS GIS Cut Line= 3
     1858758.481      382699.476     1859472.934      383038.867
     1859886.411      383619.365
#Sta/Elev= 30
       0  919.72    87.9  908.11   107.4  904.92   136.7   898.9   185.5  886.25
   244.1  873.22   263.7   870.7     293  868.35   419.9  864.92   585.9  864.57
   673.8  861.98   693.3  858.96   703.1  858.71   722.6  861.97   732.4  862.66
   820.3  860.83   849.6  860.87   908.1  858.11  1083.9  852.12  1122.9  849.26
  1152.2  844.43  1171.7   843.8  1210.8  843.96  1269.4  850.42  1279.1  850.85
  1376.8  849.12  1396.3   850.2  1464.6  856.83  1484.1  857.34  1503.7  856.76
#Mann= 3 , 0 , 0
       0      .1       0  1152.2    .045       0  1210.8      .1       0
Bank Sta=1152.2,1210.8
XS Rating Curve= 0 ,0
Exp/Cntr=0.3,0.1

Type RM Length L Ch R = 1 ,34963.5 ,200.5,199.4,198.3
XS GIS Cut Line= 4
     1858503.273      383360.934     1859258.734      383487.455
     1859790.925      383523.879      1859871.22      383625.875
#Sta/Elev= 30
       0 1071.92    49.1 1085.09    58.9 1084.12    98.2 1067.02   186.6 1023.12
   196.4  1019.5   206.2 1018.63   353.5  1054.6   363.4 1056.53   373.2 1055.87
   540.1  970.76   549.9  970.31   579.4  975.88   638.3  990.09   648.1  990.51
     658     988   756.2  945.57   804.8  930.98   872.7  918.88   911.5  906.93
   950.3  884.98   998.8  849.97  1008.4  844.98  1018.2  842.75  1027.8   842.6
  1076.3   842.7  1221.8  848.94    1318  848.49  1382.9   855.1  1429.2  856.67
#Mann= 3 , 0 , 0
       0      .1       0  1018.2    .045       0  1076.3      .1       0
Bank Sta=1018.2,1076.3
XS Rating Curve= 0 ,0
Exp/Cntr=0.3,0.1

Type RM Length L Ch R = 1 ,34764.1 ,410.5,394.6,378.7
XS GIS Cut Line= 2
     1859339.536       383699.66      1860023.13      383712.681
#Sta/Elev= 30
       0  964.82     9.8  959.03    19.5  953.65    29.3  948.41    39.1  942.48
    48.8  935.68    78.1  914.22   107.4  893.23   136.7  872.76   146.5  866.17
   175.8  847.05  182.91  843.93   185.6  843.23   195.4  842.58   234.4  842.66
   244.2  842.81   273.5  844.87   312.6  847.52   322.3  847.87   400.5  848.02
   439.5  847.72   449.3  847.99   459.1  848.97   498.1  854.26   507.9  855.43
   517.7   856.1   556.7   857.1   615.4  858.29   644.6  858.71   683.7  858.94
#Mann= 3 , 0 , 0
       0      .1       0  182.91    .045       0   273.5      .1       0
Bank Sta=182.91,273.5
XS Rating Curve= 0 ,0
Exp/Cntr=0.3,0.1

Type RM Length L Ch R = 1 ,34369.6 ,364.6,351,337.5
XS GIS Cut Line= 2
     1859623.824      384142.368     1860148.998      383712.681
#Sta/Elev= 30
       0  948.67    29.5  925.88    68.8  896.46    78.7  888.75    88.5  879.27
    98.3   869.3   108.2  859.51     118  850.58   127.8  842.87   137.7  839.37
   147.5     839   186.8  839.11   196.7     840   216.4  843.32   226.2  844.08
     236  844.29   265.5  844.35     354  844.32   363.9  844.62   373.7  845.67
   403.2  851.49     413  853.14   422.9     854   570.4  856.67   599.9  857.32
   609.7  857.84   639.2  861.56   658.9  865.34   668.7  866.93   678.6  868.12
#Mann= 3 , 0 , 0
       0      .1       0   127.8    .045       0   186.8      .1       0
Bank Sta=127.8,186.8
XS Rating Curve= 0 ,0
Exp/Cntr=0.3,0.1

Type RM Length L Ch R = 1 ,34018.5 ,255.3,244.7,234
XS GIS Cut Line= 3
     1860049.171      384376.743     1860040.491      384231.344
      1860183.72      383745.233
#Sta/Elev= 30
       0  925.07    19.4  915.99    38.8  907.46    77.7  891.66    97.1  883.43
   106.8  878.84   116.5  873.26   126.2  868.02     136   863.7   145.7  856.03
   155.4  844.15  161.82  839.74   165.2  838.18   174.9  837.81   204.1  837.64
   213.9  837.83   233.4  838.91   272.4   841.6   282.1  842.11   350.3   842.8
   360.1  843.19     399  845.36   496.5  849.35   506.2  849.98   545.2  853.21
     555  853.88   584.2  855.31   632.9  858.23   642.7  859.01   652.4  860.17
#Mann= 3 , 0 , 0
       0      .1       0  161.82    .045       0   213.9      .1       0
Bank Sta=161.82,213.9
XS Rating Curve= 0 ,0
Exp/Cntr=0.3,0.1

Type RM Length L Ch R = 1 ,33773.9 ,82,81.9,81.8
XS GIS Cut Line= 4
     1860313.928      384502.611     1860316.098      384344.191
     1860259.675        384016.5     1860201.081      383803.827
#Sta/Elev= 30
       0  863.71      28  863.71    65.2  863.01   111.8  862.02   158.4  860.36
     178  861.53   207.3  864.13   217.1  863.02   226.9  857.59   236.7  849.36
   246.4  841.98   256.2  837.47     266  835.78   285.6  834.33   314.9   833.9
   334.5  833.96   344.2  834.27     354  835.72   363.8  838.06   373.6  839.47
   432.3  843.84   461.6  845.04   471.4  845.87   481.2  846.79   519.7  852.11
   538.9     854   548.5  854.58   577.3  855.08   673.2  854.73   711.6  855.73
#Mann= 3 , 0 , 0
       0      .1       0   285.6    .045       0   344.2      .1       0
Bank Sta=285.6,344.2
XS Rating Curve= 0 ,0
Exp/Cntr=0.3,0.1

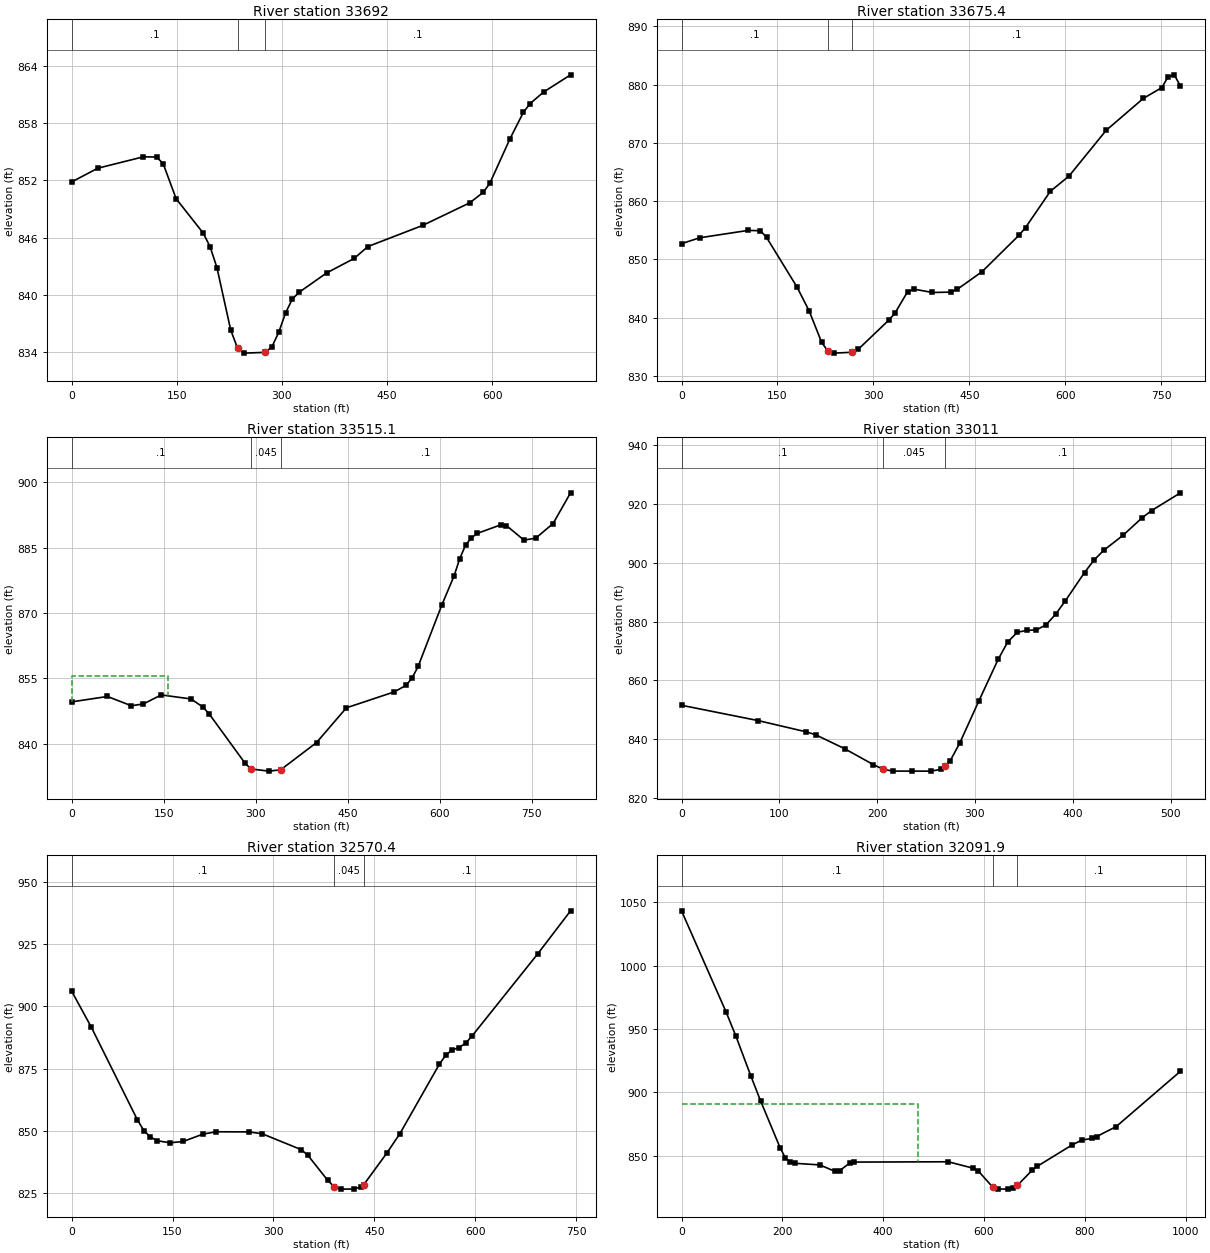
Type RM Length L Ch R = 1 ,33692   ,15.9,16.5,17.2
XS GIS Cut Line= 4
     1860387.713      384472.229     1860389.883      384313.809
      1860333.46      383986.118     1860274.866      383773.445
#Sta/Elev= 30
       0  851.84    37.3  853.28   102.5  854.48   121.2  854.45   130.5  853.77
   149.1  850.08   187.8  846.47   197.6  845.03   207.3  842.85   226.9  836.32
   236.7  834.41   246.4   833.9   275.8  833.98   285.6  834.55   295.4  836.08
   305.1  838.11   314.9  839.58   324.7  840.29   363.8  842.31   402.9  843.82
   422.5  845.07   500.5  847.28   567.7  849.65   586.9  850.74   596.4  851.69
   625.2  856.37   644.4  859.15     654  860.06   673.2  861.27   711.6  863.07
#Mann= 3 , 0 , 0
       0      .1       0   236.7    .045       0   275.8      .1       0
Bank Sta=236.7,275.8
XS Rating Curve= 0 ,0
Exp/Cntr=0.3,0.1

Type RM Length L Ch R = 1 ,33675.4 ,156.6,160.3,164.1
XS GIS Cut Line= 5
     1860396.394      384465.719     1860402.904      384313.809
     1860376.862      384133.688     1860376.862      383929.695
     1860418.095      383690.979
#Sta/Elev= 30
       0  852.69    28.5   853.7   104.5  854.97   123.5   854.9     133  853.76
   180.8  845.21   199.9  841.07   219.1  835.76   228.7  834.28   238.3   833.9
     267  834.05   276.6  834.58   324.5   839.6     334   840.8   353.5  844.44
   363.2  844.89   392.3  844.31   421.5  844.37   431.2  844.85     470  847.88
   528.3  854.19     538  855.45   576.8  861.68   605.9  864.28     664  872.13
   722.2  877.62   751.2  879.48   760.9  881.33   770.6  881.67   780.3  879.73
#Mann= 3 , 0 , 0
       0      .1       0   228.7    .045       0     267      .1       0
Bank Sta=228.7,267
XS Rating Curve= 0 ,0
Exp/Cntr=0.3,0.1

Type RM Length L Ch R = 1 ,33515.1 ,468.2,504.1,539.9
XS GIS Cut Line= 3
     1860541.793      384554.695     1860550.473      383931.865
     1860596.046      383747.403
#Sta/Elev= 30
       0  849.62    58.4  850.86    97.3  848.74   116.8  849.14     146  851.22
   194.6  850.29   214.1  848.41   223.8  846.92   282.2  835.63     292  834.24
   321.2  833.74   340.6  834.04     399  840.29   447.7  848.26   525.6  851.91
     545  853.42   554.8  855.13   564.5  857.74   603.4  871.93   622.9  878.44
   632.4   882.5   641.9   885.6   651.4  887.26   660.9  888.27   698.9  890.21
   708.4  890.06   736.9  886.74   755.9  887.15   784.4  890.52   812.9  897.57
#Mann= 3 , 0 , 0
       0      .1       0     292    .045       0   340.6      .1       0
#XS Ineff= 2 , 0
          156.78  855.45
Permanent Ineff=
       F       F
Bank Sta=292,340.6
XS Rating Curve= 0 ,0
Exp/Cntr=0.3,0.1

Type RM Length L Ch R = 1 ,33011   ,431.7,440.6,449.4
XS GIS Cut Line= 2
      1860496.22      384591.587     1861006.203      384600.268
#Sta/Elev= 30
       0  851.47    78.5  846.24   127.5  842.42   137.3   841.4   166.8  836.67
   196.2  831.24     206  829.71   215.8  829.05   235.4  829.04     255  829.04
   264.8  829.62  269.44  830.87   274.6  832.49   284.4  838.58   304.1  853.02
   323.7   867.1   333.5  873.03   343.3  876.33   353.1  876.98   362.9  877.15
   372.7  878.88   382.5  882.49   392.4  887.04     412  896.68   421.8  900.95
   431.6  904.24   451.2  909.31   470.8   915.3   480.6  917.79   510.1  923.83
#Mann= 3 , 0 , 0
       0      .1       0     206    .045       0  269.44      .1       0
Bank Sta=206,269.44
XS Rating Curve= 0 ,0
Exp/Cntr=0.3,0.1

Type RM Length L Ch R = 1 ,32570.4 ,488.1,478.6,469.1
XS GIS Cut Line= 2
     1860213.234      384847.663     1860893.789      385142.802
#Sta/Elev= 30
       0   906.2    29.3  891.65    97.6  854.46   107.4  850.02   117.1  847.47
   126.9  845.96   146.4  845.11   165.9  845.66   195.2   848.6   214.7  849.55
   263.5   849.5     283  848.79   341.6  842.33   351.4  840.03   380.7  830.02
   390.4   827.4   400.2  826.46   419.7   826.5   429.5  827.34  434.37  828.27
   468.5  840.92     488  848.76   546.6  876.68   556.4  880.48   566.1  882.52
   575.9  883.46   585.6  885.16   595.4  888.14     693   921.2   741.8  938.51
#Mann= 3 , 0 , 0
       0      .1       0   390.4    .045       0  434.37      .1       0
Bank Sta=390.4,434.37
XS Rating Curve= 0 ,0
Exp/Cntr=0.3,0.1

Type RM Length L Ch R = 1 ,32091.9 ,709.3,700.9,692.6
XS GIS Cut Line= 2
     1859928.512      385493.497     1860918.095       385483.08
#Sta/Elev= 30
       0 1043.13    88.2  963.56   107.8  944.44   137.2  913.24   156.8  893.29
     196  855.94   205.8  848.55   215.6  844.92   225.4  844.08   274.4  842.81
   303.8  837.82   313.6  838.24   333.2   844.2   342.9  845.05   529.1  845.29
   578.1  840.25   587.9  838.35   617.3  825.28   627.1  823.82   646.7  823.73
   656.5  824.34   666.3  826.71   695.7  838.74   705.5   841.7   774.1  858.44
   793.7  862.37   813.3  863.69   823.1   865.1   862.3   873.1   989.6  916.67
#Mann= 3 , 0 , 0
       0      .1       0   617.3    .045       0   666.3      .1       0
#XS Ineff= 2 , 0
          469.44  890.56
Permanent Ineff=
       F       F
Bank Sta=617.3,666.3
XS Rating Curve= 0 ,0
Exp/Cntr=0.3,0.1