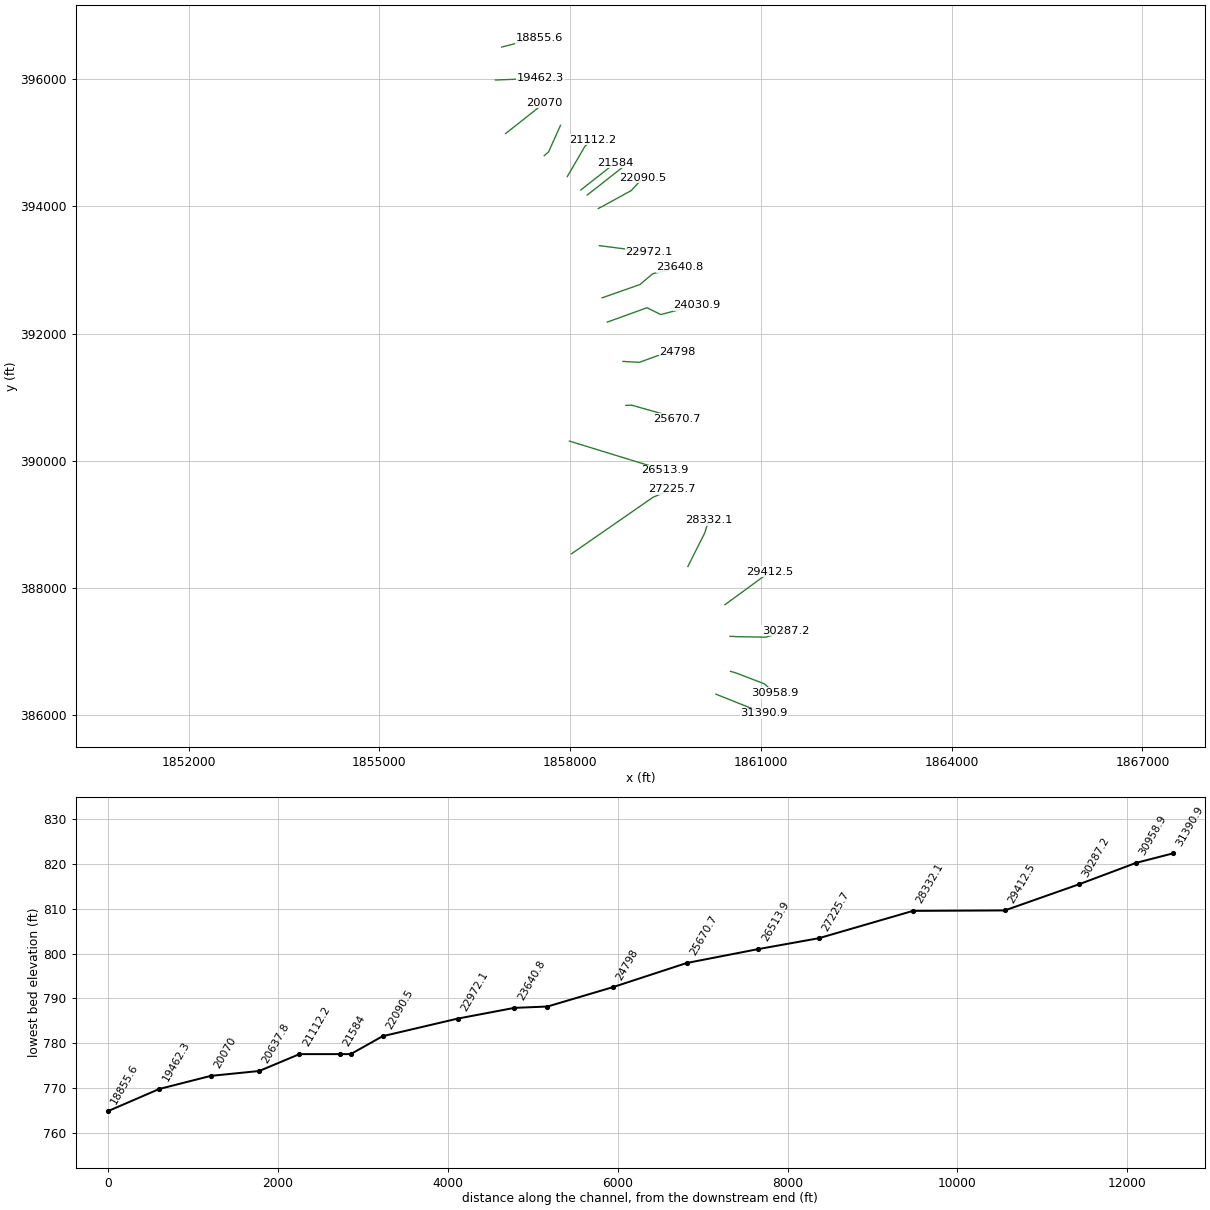
HEC-RAS study PAINTCK.prj: PAINTCK

--- PAINTCK.g01 (geometry) --- (continued)

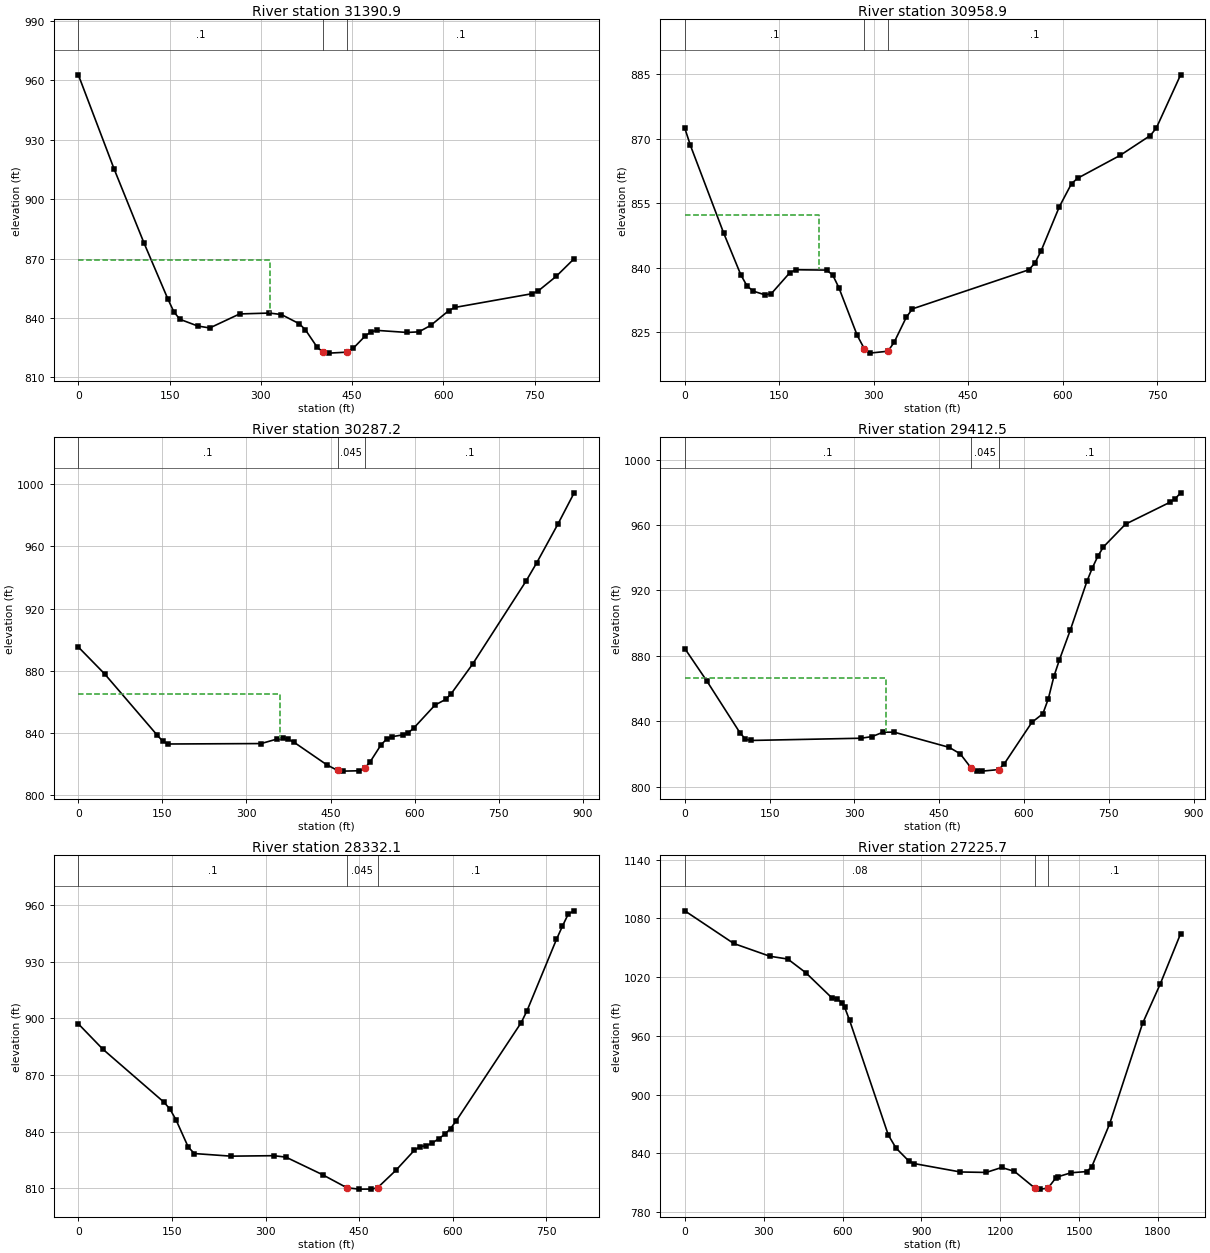
Type RM Length L Ch R = 1 ,31390.9 ,431.6,432,432.4
XS GIS Cut Line= 2
     1860293.095      386333.775     1861050.039      386031.691
#Sta/Elev= 30
       0   962.8    58.9  915.19     108  877.86   147.3  849.54   157.1  843.12
   166.9  839.39   196.4  835.98     216  835.01   265.1  842.08   314.2  842.53
   333.8  841.78   363.3  837.11   373.1  834.14   392.8  825.18   402.6  822.74
   412.4   822.3   441.9   822.8   451.7  824.69   471.3  830.89   481.1  833.09
     491  833.78   540.1  832.74   559.7  833.04   579.3  836.31   608.8  843.73
   618.6  845.35   746.3  852.33   756.1  853.74   785.5  861.07     815  869.98
#Mann= 3 , 0 , 0
       0      .1       0   402.6    .045       0   441.9      .1       0
#XS Ineff= 2 , 0
          314.44  869.18
Permanent Ineff=
       F       F
Bank Sta=402.6,441.9
XS Rating Curve= 0 ,0
Exp/Cntr=0.3,0.1

Type RM Length L Ch R = 1 ,30958.9 ,663.9,671.8,679.7
XS GIS Cut Line= 4
     1860522.262      386691.413     1860598.651       386670.58
     1861053.512      386496.969     1861220.178      386351.136
#Sta/Elev= 30
       0  872.43     8.8  868.48    61.6  848.13    88.9  838.41    98.6  835.85
   108.4  834.61   127.9  833.71   137.6  834.04   166.8  838.87   176.6  839.56
   225.2  839.48     235  838.32   244.7   835.4   273.9   824.3     285  821.25
   293.4   820.2   322.6  820.64   332.4  822.69   351.8  828.53   361.6  830.48
   546.6  839.56   556.3  841.17     566  843.98   594.9   854.2   614.2  859.55
   623.8   860.8   691.2   866.1   739.4  870.73     749  872.49   787.5  884.82
#Mann= 3 , 0 , 0
       0      .1       0     285    .045       0   322.6      .1       0
#XS Ineff= 2 , 0
          212.58  852.32
Permanent Ineff=
       F       F
Bank Sta=285,322.6
XS Rating Curve= 0 ,0
Exp/Cntr=0.3,0.1

Type RM Length L Ch R = 1 ,30287.2 ,860,874.6,889.3
XS GIS Cut Line= 4
     1860515.317      387243.497     1860636.845      387236.552
     1861084.762      387229.608     1861383.373      387330.302
#Sta/Elev= 30
       0  895.26    46.8  878.02   141.2  838.37   150.9  834.61   160.7  832.88
   326.2  833.16   355.4  836.16   365.2  836.46   374.9  835.82   384.7  834.05
   443.1  819.57   462.6  815.87   472.3  815.43   501.5  815.67   511.3  817.29
     521  821.56   540.5  832.52   550.2  836.03     560  837.59   579.2  838.76
   588.8  840.13   598.3  843.03   636.5  857.93   655.6  861.58   665.2  865.14
   703.4  884.18   798.9  937.65     818  949.44   856.2  974.61   884.8  994.45
#Mann= 3 , 0 , 0
       0      .1       0   462.6    .045       0   511.3      .1       0
#XS Ineff= 2 , 0
           360.5  865.31
Permanent Ineff=
       F       F
Bank Sta=462.6,511.3
XS Rating Curve= 0 ,0
Exp/Cntr=0.3,0.1

Type RM Length L Ch R = 1 ,29412.5 ,1069.7,1080.4,1091
XS GIS Cut Line= 2
     1860435.456      387740.025     1861143.789      388257.386
#Sta/Elev= 30
       0  884.52      39  864.66    97.5  833.07   107.2  829.17     117  828.34
   311.9   829.7   331.4  830.72   350.9   833.4   370.4   833.4   467.8  824.12
   487.3  820.17   506.8   811.4   516.6  809.77   526.3   809.6   555.5  810.55
   565.3  814.13     614  839.39   633.5  844.66   643.2  853.88     653  867.45
   662.7  877.52   682.2  895.94   711.5  925.63   721.2  933.92     731   941.1
   740.7  946.62   779.7  960.49   857.7  973.76   867.4  975.95   877.2  979.64
#Mann= 3 , 0 , 0
       0      .1       0   506.8    .045       0   555.5      .1       0
#XS Ineff= 2 , 0
          355.18  866.35
Permanent Ineff=
       F       F
Bank Sta=506.8,555.5
XS Rating Curve= 0 ,0
Exp/Cntr=0.3,0.1

Type RM Length L Ch R = 1 ,28332.1 ,1117.7,1106.4,1095.3
XS GIS Cut Line= 3
     1859852.123      388340.719     1860116.012      388865.025
     1860178.512      389062.941
#Sta/Elev= 30
       0  897.07    39.1   883.7     137  855.62   146.7  851.98   156.5  846.23
   176.1  831.79   185.9  828.35   244.6  826.97     313  827.22   332.6  826.46
   391.3  817.15   430.4  810.21     450   809.5   469.6  809.52   479.4   810.2
   508.7  819.42   538.1  829.97   547.8  832.06   557.6   832.5   567.4  833.96
   577.2  836.17     587  838.49   596.4  841.62   605.8  845.82   709.6   897.7
     719  904.04   766.2  941.86   775.6  948.75   785.1   955.3   794.5  956.95
#Mann= 3 , 0 , 0
       0      .1       0   430.4    .045       0   479.4      .1       0
Bank Sta=430.4,479.4
XS Rating Curve= 0 ,0
Exp/Cntr=0.3,0.1

Type RM Length L Ch R = 1 ,27225.7 ,732.3,711.9,691.3
XS GIS Cut Line= 3
     1858022.735      388540.177     1859303.512      389427.525
     1859605.595      389555.997
#Sta/Elev= 30
       0 1087.78   186.2  1054.4   323.4 1041.39     392  1038.5   460.6 1024.48
   558.6  999.08   578.2  998.02   597.8  993.99   607.6  989.63   627.2  975.72
   774.2  858.74   803.6  845.37   852.6  832.04   872.2  829.54  1048.6  820.94
  1146.6  820.48  1205.4  825.53  1254.3  821.54  1332.7  804.29  1352.3  803.42
  1381.7  804.34  1411.1  814.73  1420.9  816.19  1469.9  820.16  1528.7  821.35
  1548.3  826.25  1616.1  869.92  1741.6  972.75  1809.2 1013.24  1886.4 1064.46
#Mann= 3 , 0 , 0
       0     .08       0  1332.7    .045       0  1381.7      .1       0
Bank Sta=1332.7,1381.7
XS Rating Curve= 0 ,0
Exp/Cntr=0.3,0.1

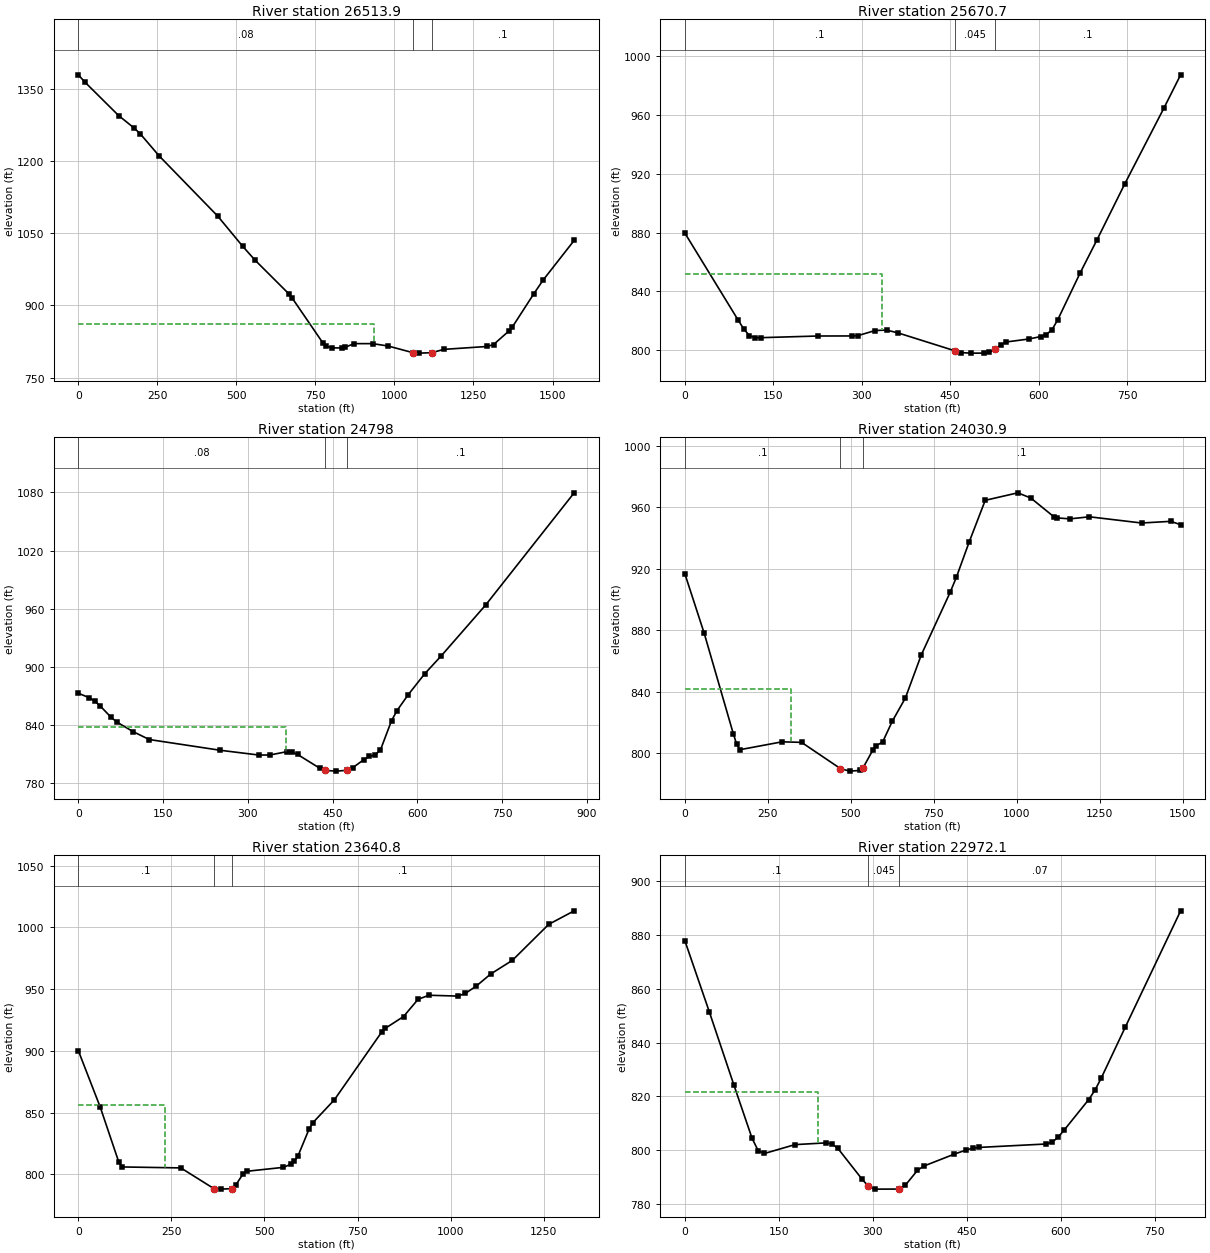
Type RM Length L Ch R = 1 ,26513.9 ,842.5,843.2,843.7
XS GIS Cut Line= 2
     1857988.013       390311.01     1859487.539      389851.136
#Sta/Elev= 30
       0 1379.21    19.6 1364.87   127.4  1294.6   176.4 1268.72   196.1 1256.49
   254.9 1211.31   441.1 1085.54   519.6 1023.22   558.8  994.32   666.6  923.73
   676.4  915.47   774.4  821.45   784.2  815.19   803.8   811.9   833.2   811.8
     843  812.93   872.5  820.74   931.3   820.7   980.3  815.74  1058.7  801.89
  1078.3     801  1117.5  801.89  1156.7  808.83    1294  814.86  1313.6  818.88
  1362.6  847.23  1372.4  854.69    1441  924.43  1470.4  952.87  1568.5 1035.17
#Mann= 3 , 0 , 0
       0     .08       0  1058.7    .045       0  1117.5      .1       0
#XS Ineff= 2 , 0
          936.76  861.99
Permanent Ineff=
       F       F
Bank Sta=1058.7,1117.5
XS Rating Curve= 0 ,0
Exp/Cntr=0.3,0.1

Type RM Length L Ch R = 1 ,25670.7 ,858.4,872.7,886.6
XS GIS Cut Line= 4
     1858876.428      390871.969     1858966.706      390875.441
     1859497.956      390726.136     1859685.456      390660.163
#Sta/Elev= 30
       0  879.72    90.3  820.52     100  814.36   109.7  809.77   119.4  808.46
   129.1  808.43   225.9  809.56     284   809.6   293.6  809.82   322.7  813.28
   342.1   813.6   361.4   811.7   458.2  799.47   467.9  798.27   484.9   797.9
   506.6   797.9   516.3  798.42     526  800.49   535.7  803.42   545.4  805.51
   584.1  807.55   603.4  809.17   613.1  810.54   622.8  813.84   632.5  820.63
   670.6   852.6     699  875.01   746.3  913.28   812.6  964.82   840.9  987.44
#Mann= 3 , 0 , 0
       0      .1       0   458.2    .045       0     526      .1       0
#XS Ineff= 2 , 0
          334.81  852.04
Permanent Ineff=
       F       F
Bank Sta=458.2,526
XS Rating Curve= 0 ,0
Exp/Cntr=0.3,0.1

Type RM Length L Ch R = 1 ,24798   ,767.3,767.2,767.1
XS GIS Cut Line= 4
     1858831.289      391562.941     1859091.706      391549.052
     1859376.428      391653.219     1859685.456      391705.302
#Sta/Elev= 30
       0   872.8    19.3  868.19      29  864.77    38.6  859.73      58  847.99
    67.6  843.34    96.6   833.3   125.6  825.07   251.1  814.01   319.5  809.08
     339  809.14   368.4  812.48   378.2  812.02   387.9  809.71     427  795.57
   436.8  793.25   455.8   792.5     476  793.33   485.7  796.11   505.3  804.38
   515.1  807.78   524.8  809.04   534.6   814.3   554.2  844.49     564  854.97
   583.6  871.21   612.9  892.86   642.3  911.42   720.7  963.74   877.4 1079.47
#Mann= 3 , 0 , 0
       0     .08       0   436.8    .045       0     476      .1       0
#XS Ineff= 2 , 0
          367.58  838.39
Permanent Ineff=
       F       F
Bank Sta=436.8,476
XS Rating Curve= 0 ,0
Exp/Cntr=0.3,0.1

Type RM Length L Ch R = 1 ,24030.9 ,390.3,390,389.8
XS GIS Cut Line= 4
     1858584.762      392180.997     1859209.762      392406.691
     1859425.039      392299.052     1859994.484      392448.358
#Sta/Elev= 30
       0  916.78    58.6  877.83   146.6  812.22   156.4   805.6   166.1  802.15
   293.2  807.28   351.8  806.92   469.1  789.82   496.8   788.2   527.7  788.64
   537.5  790.54   566.8  801.99   576.6  804.69   596.1  807.17   625.4  820.77
   664.5  835.76   712.6   863.9   799.3  904.48   818.5  914.53     857  937.45
   905.2  964.47  1003.3  969.34  1042.6  965.95  1111.2   953.9    1121  953.03
  1160.3  952.39  1219.2  953.74  1376.1   949.7  1464.4  950.78  1493.9  948.58
#Mann= 3 , 0 , 0
       0      .1       0   469.1    .045       0   537.5      .1       0
#XS Ineff= 2 , 0
          318.87  841.52
Permanent Ineff=
       F       F
Bank Sta=469.1,537.5
XS Rating Curve= 0 ,0
Exp/Cntr=0.3,0.1

Type RM Length L Ch R = 1 ,23640.8 ,679.2,668.7,658.2
XS GIS Cut Line= 4
     1858504.901      392562.941     1859098.651      392771.275
     1859300.039      392941.413     1859727.123      393042.108
#Sta/Elev= 30
       0  900.13      59  854.24   108.2  810.22     118  805.88   275.3   805.1
   363.8  788.37   383.4   787.9   412.9  788.34   422.8  791.17   442.4  800.25
   452.3  802.36   550.6  805.55   570.2  807.98   580.1  810.46   589.9  814.79
   619.4  836.31   629.2  841.52   687.8  860.37   814.8  915.25   824.5  918.28
   873.4  927.79   912.4  941.75   941.6  945.06  1019.6  944.39  1039.1   946.5
  1068.4   952.4  1107.4  962.26  1165.9   973.4  1263.4 1002.54  1331.7  1013.5
#Mann= 3 , 0 , 0
       0      .1       0   363.8    .045       0   412.9      .1       0
#XS Ineff= 2 , 0
          231.89  856.38
Permanent Ineff=
       F       F
Bank Sta=363.8,412.9
XS Rating Curve= 0 ,0
Exp/Cntr=0.3,0.1

Type RM Length L Ch R = 1 ,22972.1 ,867.1,881.6,896.1
XS GIS Cut Line= 2
     1858459.762      393382.386     1859244.484      393281.691
#Sta/Elev= 30
       0  877.95    39.1  851.44    78.1  824.39   107.4  804.36   117.2  799.75
     127  798.75   175.8  802.05   224.6  802.69   234.4  802.36   244.2  800.67
   283.2   789.1     293  786.56   302.8   785.5   341.9  785.52   351.6  786.86
   371.2  792.46   380.9  794.03   429.8  798.49   449.3  800.08   459.1  800.72
   468.8     801   576.3  802.28     586  802.91   595.8  804.83   605.6  807.53
   644.6  818.82   654.4  822.26   664.2  826.64   703.2  845.89   791.2  888.99
#Mann= 3 , 0 , 0
       0      .1       0     293    .045       0   341.9     .07       0
#XS Ineff= 2 , 0
          212.58  821.79
Permanent Ineff=
       F       F
Bank Sta=293,341.9
XS Rating Curve= 0 ,0
Exp/Cntr=0.3,0.1

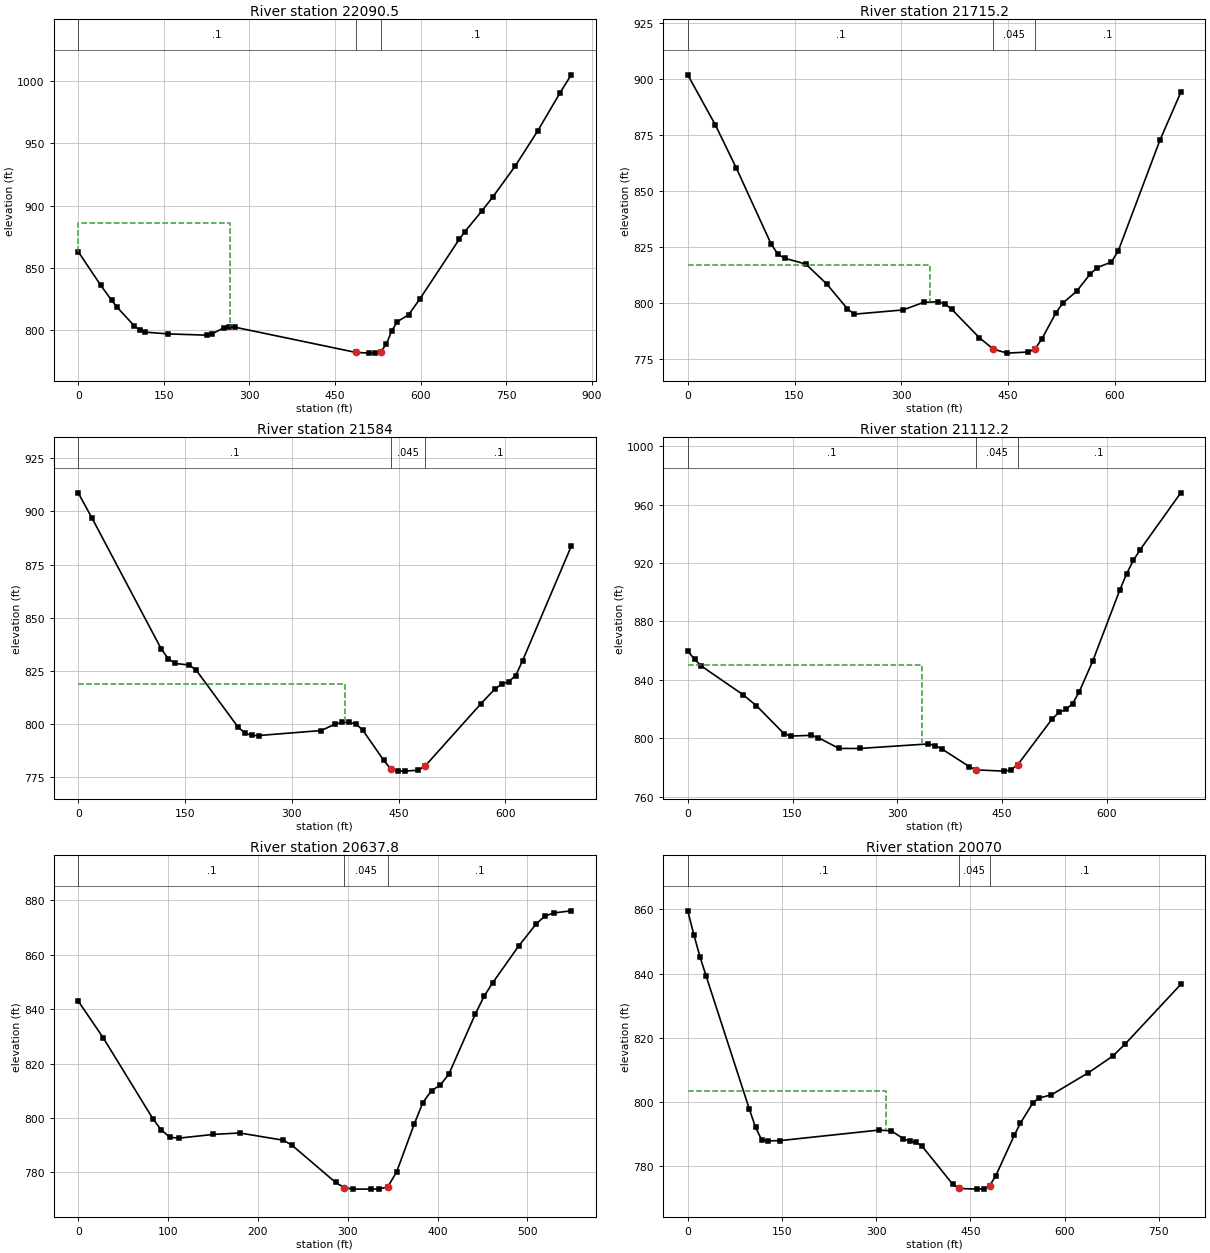
Type RM Length L Ch R = 1 ,22090.5 ,372.9,375.3,377.1
XS GIS Cut Line= 4
     1858442.401      393965.719     1858529.206      394010.858
     1858959.762      394246.969     1859147.262      394448.358
#Sta/Elev= 30
       0  863.05    39.1  836.32    58.7  823.88    68.5  818.26    97.8  803.71
   107.7  800.11   117.5  798.45   156.8  797.04   225.5     796   235.3  797.23
     255  801.86   264.8  802.62   274.6  802.41   486.1  782.21   510.3  781.59
   520.1   781.6     530  782.61   539.8   788.6   549.6  799.64   559.4  806.88
   579.1  812.41   598.7  825.02   667.5  872.81   677.3   878.9   706.8  895.33
   726.5  906.87   765.8   931.7   805.1  959.84   844.4  990.49     864 1004.95
#Mann= 3 , 0 , 0
       0      .1       0   486.1    .045       0     530      .1       0
#XS Ineff= 2 , 0
          265.72  886.22
Permanent Ineff=
       F       F
Bank Sta=486.1,530
XS Rating Curve= 0 ,0
Exp/Cntr=0.3,0.1

Type RM Length L Ch R = 1 ,21715.2 ,129.7,131.2,132.7
XS GIS Cut Line= 2
     1858268.789      394177.525     1858813.928      394604.608
#Sta/Elev= 30
       0  901.85      39  879.37    68.3  860.19     117  826.39   126.8  821.69
   136.6  819.91   165.8  817.38   195.1  808.52   224.3  797.38   234.1     795
   302.4  796.88   331.6  800.29   351.1  800.53   360.9  799.68   370.6  797.24
   409.7  784.46   429.2  779.38   448.7   777.6   477.9   778.1   487.7   779.4
   497.4  783.95     517   795.5   526.7   799.9   546.2  805.21   565.7  813.07
   575.5  815.81     595  818.26   604.7  823.23   663.2  872.63   692.5  894.02
#Mann= 3 , 0 , 0
       0      .1       0   429.2    .045       0   487.7      .1       0
#XS Ineff= 2 , 0
          339.77  817.14
Permanent Ineff=
       F       F
Bank Sta=429.2,487.7
XS Rating Curve= 0 ,0
Exp/Cntr=0.3,0.1

Type RM Length L Ch R = 1 ,21584   ,463.3,471.8,480.4
XS GIS Cut Line= 2
     1858168.095      394257.386     1858713.234      394684.469
#Sta/Elev= 30
       0   908.8    19.5  896.84     117  834.98   126.8   830.5   136.6  828.34
   156.1  827.62   165.8  825.18   224.3  798.46   234.1  795.57   243.8  794.44
   253.6  794.38   341.4  796.74   360.9  799.78   370.6  800.55   380.4  800.57
   390.2  799.84   399.9  796.84   429.2  782.66   438.9   778.7   448.7  777.72
   458.4   777.6   477.9  778.05   487.7  780.17   565.7  809.38   585.2  816.32
     595  818.61   604.7   819.8   614.5  822.66   624.2  829.68   692.5  883.59
#Mann= 3 , 0 , 0
       0      .1       0   438.9    .045       0   487.7      .1       0
#XS Ineff= 2 , 0
          374.49  818.57
Permanent Ineff=
       F       F
Bank Sta=438.9,487.7
XS Rating Curve= 0 ,0
Exp/Cntr=0.3,0.1

Type RM Length L Ch R = 1 ,21112.2 ,471.9,474.4,476.8
XS GIS Cut Line= 3
     1857956.289      394469.191     1858234.067      394944.886
     1858348.651      395049.052
#Sta/Elev= 30
       0  859.86     9.8  854.02    19.7  849.46    78.7  830.03    98.4  822.35
   137.7  803.27   147.6   801.6   177.1  802.09   186.9   800.5   216.4  793.12
   245.9   793.1   344.3  796.22   354.1   795.1     364  792.68   403.3  780.63
   413.1  778.44   452.5   777.6   462.3  778.32   472.2  781.89   521.4   813.2
   531.2  817.72     541  819.77   550.9  823.82   560.5     832   579.9  853.16
   618.6  901.72   628.3  912.76     638  921.92   647.6  929.13   705.7  968.02
#Mann= 3 , 0 , 0
       0      .1       0   413.1    .045       0   472.2      .1       0
#XS Ineff= 2 , 0
          335.16  850.13
Permanent Ineff=
       F       F
Bank Sta=413.1,472.2
XS Rating Curve= 0 ,0
Exp/Cntr=0.3,0.1

Type RM Length L Ch R = 1 ,20637.8 ,578.8,567.8,556.9
XS GIS Cut Line= 3
     1857593.095      394796.448     1857662.539      394857.212
     1857849.171      395273.879
#Sta/Elev= 30
       0  843.04    27.7  829.58      83   799.8    92.3  795.65     102  792.94
   111.7  792.58   150.6  793.97   179.7  794.49   228.3  791.83     238  789.98
   286.6  776.28   296.3  774.37     306  773.86   325.4  773.84   335.1  773.84
   344.8  774.75   354.6   780.3     374  797.72   383.7   805.7   393.4  810.11
   403.1  812.08   412.8  816.31     442  838.21   451.7  844.71   461.4  849.76
   490.6  863.38     510  871.48   519.7  874.33   529.4  875.42   548.8   876.2
#Mann= 3 , 0 , 0
       0      .1       0   296.3    .045       0   344.8      .1       0
Bank Sta=296.3,344.8
XS Rating Curve= 0 ,0
Exp/Cntr=0.3,0.1

Type RM Length L Ch R = 1 ,20070   ,622,607.7,593.4
XS GIS Cut Line= 2
     1856985.456       395143.67     1857601.776      395629.782
#Sta/Elev= 30
       0  859.58     9.8   852.1    19.6  845.14    29.4  839.18    98.1  797.71
   107.9  792.05   117.7  788.13   127.6  787.81   147.2   787.9   304.2  791.18
   323.8  790.96   343.4  788.51   353.2  787.68     363  787.38   372.8  786.24
   421.9  774.28   431.7  772.98   461.2  772.76     471  772.83   480.8  773.83
   490.6  776.99     520   789.6   529.8  793.38   549.5  799.65   559.3  801.19
   578.9  802.16   637.8  809.05     677  814.31   696.6  818.06     785  836.63
#Mann= 3 , 0 , 0
       0      .1       0   431.7    .045       0   480.8      .1       0
#XS Ineff= 2 , 0
          315.32  803.49
Permanent Ineff=
       F       F
Bank Sta=431.7,480.8
XS Rating Curve= 0 ,0
Exp/Cntr=0.3,0.1

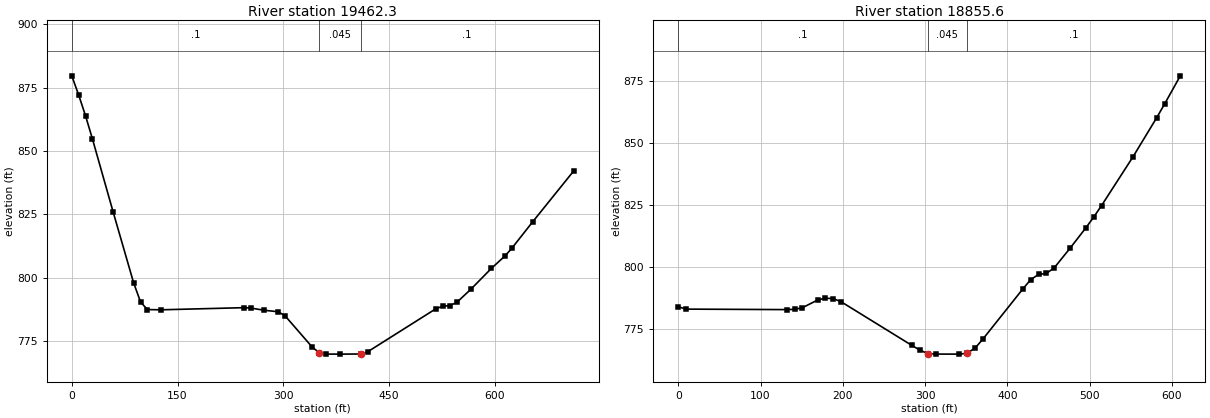
Type RM Length L Ch R = 1 ,19462.3 ,600.2,606.7,613.1
XS GIS Cut Line= 2
     1856824.866      395985.684     1857536.671      396011.726
#Sta/Elev= 30
       0  879.66     9.8  872.09    19.5  863.91    29.3  854.78    58.5  826.12
    87.8  797.94    97.6  790.41   107.3  787.42   126.8  787.33   243.9  788.17
   253.7  788.04   273.2  787.14   292.7  786.57   302.5  784.99   341.5  772.49
   351.3  770.42     361  769.86   380.2  769.84   409.8  769.89   419.6  770.73
   517.1  787.84   526.9  788.76   536.6  788.99   546.4   790.3   565.9  795.36
   595.2  803.64   614.7  808.61   624.5  811.68   653.7  821.98   712.3   842.2
#Mann= 3 , 0 , 0
       0      .1       0   351.3    .045       0   409.8      .1       0
Bank Sta=351.3,409.8
XS Rating Curve= 0 ,0
Exp/Cntr=0.3,0.1

Type RM Length L Ch R = 1 ,18855.6 ,483.7,492.4,500.6
XS GIS Cut Line= 4
     1856922.956      396502.394     1857123.477      396554.478
     1857342.227      396627.394     1857514.102      396640.415
#Sta/Elev= 30
       0  783.98     9.4     783   131.8   782.8   141.3  782.91   150.7  783.54
   169.5  786.67   178.9   787.4   188.3  787.22   197.8  785.99     284  768.37
   293.6  766.51   303.2  765.08   312.9   764.9   341.7  764.88   350.9  765.23
   360.9  767.37   370.5  771.06   418.5  791.02   428.2  794.83   437.8  796.95
   447.3  797.37   456.9  799.62   476.1   807.5   495.2  815.66   504.8  820.02
   514.4  824.69   552.7  844.36   581.4  860.05     591  865.57   610.1  876.91
#Mann= 3 , 0 , 0
       0      .1       0   303.2    .045       0   350.9      .1       0
Bank Sta=303.2,350.9
XS Rating Curve= 0 ,0
Exp/Cntr=0.3,0.1