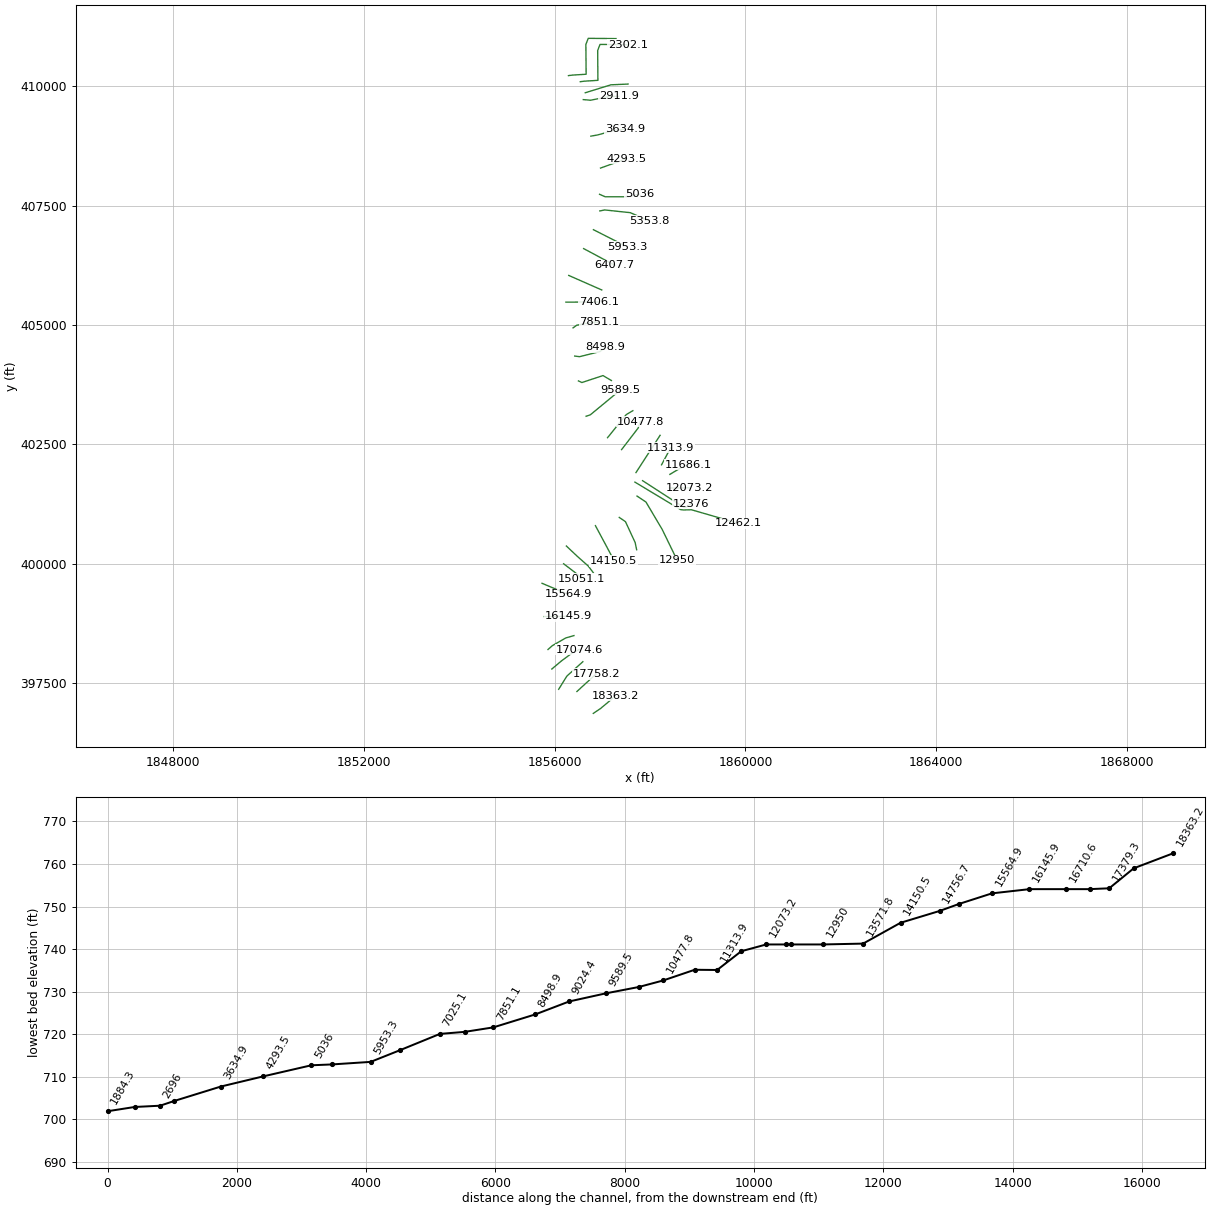
HEC-RAS study PAINTCK.prj: PAINTCK

--- PAINTCK.g01 (geometry) --- (continued)

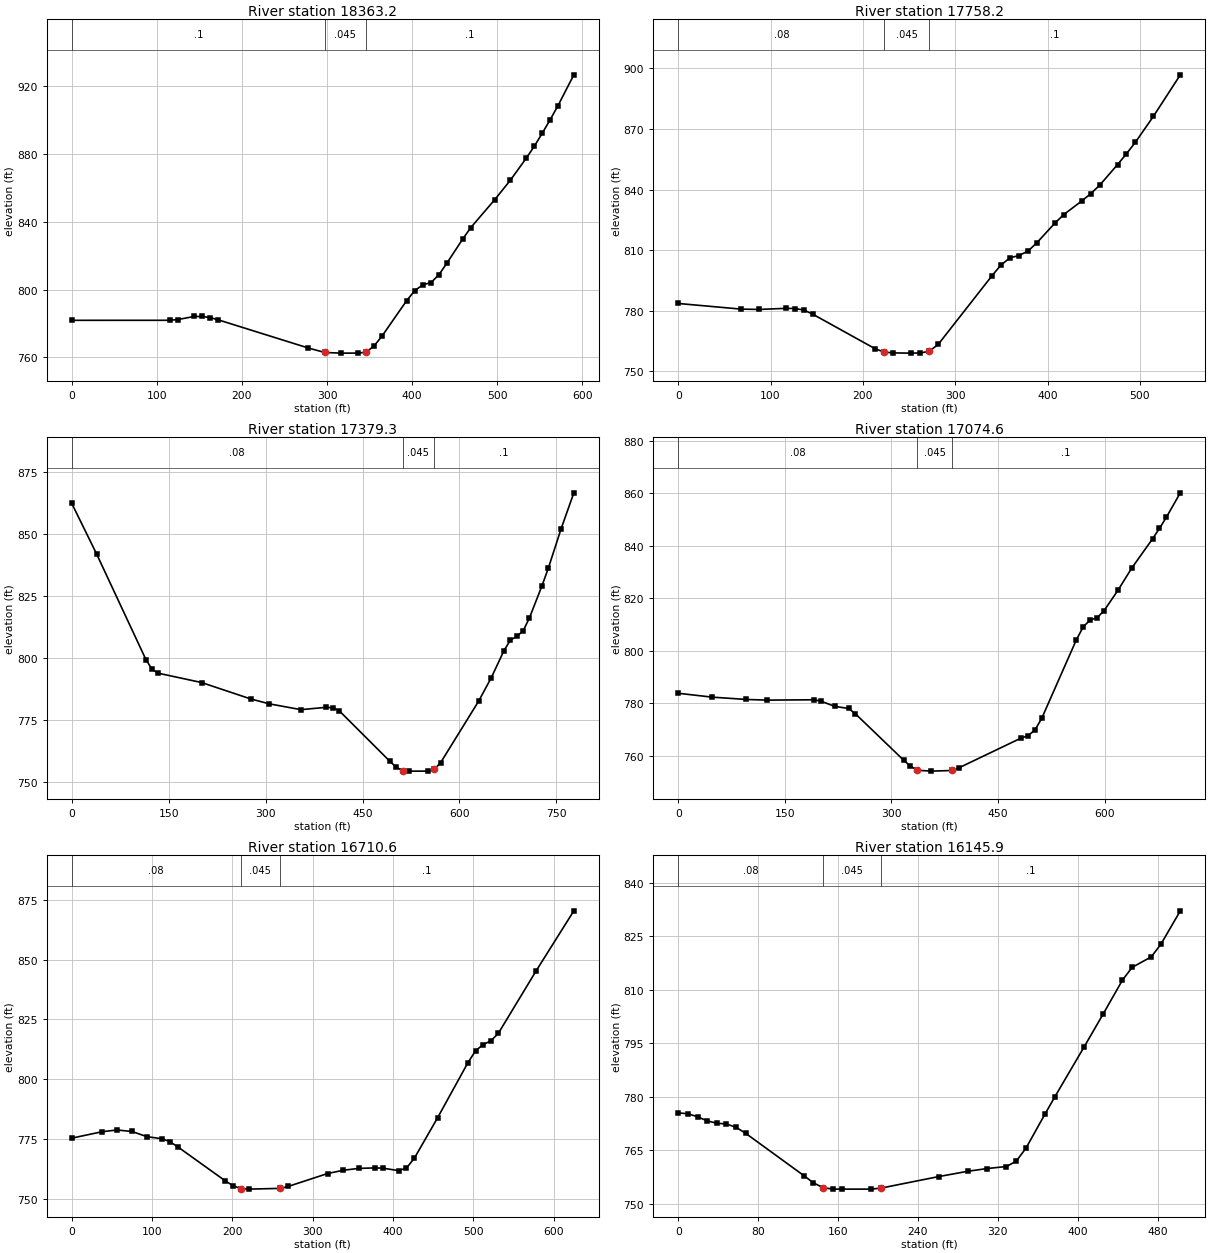
Type RM Length L Ch R = 1 ,18363.2 ,604,605.1,606.1
XS GIS Cut Line= 4
     1856808.373      396859.165     1856959.414      396960.728
      1857144.31      397114.374     1857266.706      397228.957
#Sta/Elev= 30
       0  781.88     115  781.89   124.5  782.32   143.7  784.14   153.3  784.14
   162.8  783.48   172.4  782.12   278.2  765.49   297.4  762.88   316.6   762.5
   335.9  762.52   345.5  762.96   355.1   766.6   364.7  772.61   393.6   793.5
   403.2  799.47   412.8  802.88   422.4   804.2   431.7  808.92     441  815.74
   459.7  830.04     469  836.65   496.9     853   515.6  864.67   534.2  877.65
   543.5  884.56   552.8  892.23   562.1  900.19   571.4  908.58   590.1  926.85
#Mann= 3 , 0 , 0
       0      .1       0   297.4    .045       0   345.5      .1       0
Bank Sta=297.4,345.5
XS Rating Curve= 0 ,0
Exp/Cntr=0.3,0.1

Type RM Length L Ch R = 1 ,17758.2 ,379.1,378.9,378.7
XS GIS Cut Line= 2
     1856464.623      397317.499     1856865.664      397684.686
#Sta/Elev= 30
       0  783.59      68   780.8    87.4  780.64   116.5  781.18   126.2   781.1
   135.9  780.38   145.6  778.31   213.6  761.08   223.3   759.5     233   759.1
   252.4     759     262  759.07   271.9  759.92   281.6  763.34   339.8  797.31
   349.6  802.66   359.3  806.18     369  807.35   378.7   809.5   388.4  813.65
   407.8   823.3   417.5  827.59   436.9  834.31   446.6   837.9   456.4  842.13
   475.8  852.37   485.5  857.77   495.2  863.46   514.6  876.24   543.8  896.84
#Mann= 3 , 0 , 0
       0     .08       0   223.3    .045       0   271.9      .1       0
Bank Sta=223.3,271.9
XS Rating Curve= 0 ,0
Exp/Cntr=0.3,0.1

Type RM Length L Ch R = 1 ,17379.3 ,306.8,304.7,302.5
XS GIS Cut Line= 3
      1856081.81      397364.374     1856253.685      397640.415
     1856589.623      397942.499
#Sta/Elev= 30
       0  862.38    38.3  842.04   114.8   799.3   124.3  795.37   133.9  793.83
   200.8  790.07   277.4   783.4     306  781.45   354.6  779.12   393.9  780.06
   403.8  779.87   413.6  778.75   492.1  758.32     502  755.89   511.9  754.52
   521.6   754.3   551.1   754.3   560.9  755.01   570.7  757.67   629.6  782.52
   649.3  792.05   668.9  802.96   678.8  807.19   688.6  808.69   698.4  810.89
   708.2  816.11   727.8  829.19   737.7  836.38   757.3  852.16     777  866.65
#Mann= 3 , 0 , 0
       0     .08       0   511.9    .045       0   560.9      .1       0
Bank Sta=511.9,560.9
XS Rating Curve= 0 ,0
Exp/Cntr=0.3,0.1

Type RM Length L Ch R = 1 ,17074.6 ,366.6,364,361.4
XS GIS Cut Line= 4
     1855938.581      397788.853     1856136.498      397955.519
     1856347.435      398111.769     1856511.498      398197.707
#Sta/Elev= 30
       0  783.79    47.9  782.31    95.8  781.43   124.6  781.18   191.7  781.31
   201.2  780.73   220.4  778.78   239.6  778.01   249.2  775.99   317.1   758.3
   326.8  755.96   336.5  754.43     356   754.1   385.1  754.34   394.9  755.35
   482.4   766.7   492.1  767.63   501.8  769.71   511.5  774.23   560.2  804.16
     570  809.18   579.7  811.73   589.5  812.62   599.2  815.28   618.7  823.05
   638.2  831.54   667.5  842.71   677.2  846.67     687  850.97   706.5  860.23
#Mann= 3 , 0 , 0
       0     .08       0   336.5    .045       0   385.1      .1       0
Bank Sta=336.5,385.1
XS Rating Curve= 0 ,0
Exp/Cntr=0.3,0.1

Type RM Length L Ch R = 1 ,16710.6 ,576.2,564.7,553.2
XS GIS Cut Line= 4
     1855857.852      398197.707     1855948.998      398278.436
     1856230.248      398439.894     1856402.123      398489.374
#Sta/Elev= 30
       0  775.39    37.5  778.06    56.2   778.8    74.9  778.17    93.7     776
   112.4  775.14   121.8  773.97   131.6  771.84   190.6  757.66   200.4  755.58
   210.2  754.34     220   754.1   259.3  754.41   269.2  755.21   318.3   760.6
     338  761.99   357.6  762.77   377.3  762.96   387.1  762.86   406.8  761.83
   416.6  762.91   426.4  767.02   455.5  784.01   493.1  806.93   502.5  811.84
     512  814.49   521.4  815.98   530.8   819.1   577.8  845.17   624.9  870.33
#Mann= 3 , 0 , 0
       0     .08       0   210.2    .045       0   259.3      .1       0
Bank Sta=210.2,259.3
XS Rating Curve= 0 ,0
Exp/Cntr=0.3,0.1

Type RM Length L Ch R = 1 ,16145.9 ,590.2,581,571.8
XS GIS Cut Line= 2
     1855779.727      398887.811     1856282.331      398893.019
#Sta/Elev= 30
       0  775.47     9.7  775.22    19.3  774.39      29  773.22    38.7  772.57
    48.3  772.35      58  771.41    67.7   769.7   125.7   757.9   135.3  755.87
     145   754.5   154.7  754.11   164.3   754.1   193.3   754.1     203  754.39
     261  757.63     290  759.11   309.3  759.87   328.6  760.44   338.3  761.92
     348  765.54   367.3  775.21     377  779.97     406  793.81   425.3  803.14
   444.6  812.64   454.3  816.23   473.6  819.21   483.3  822.79   502.6  832.09
#Mann= 3 , 0 , 0
       0     .08       0     145    .045       0     203      .1       0
Bank Sta=145,203
XS Rating Curve= 0 ,0
Exp/Cntr=0.3,0.1

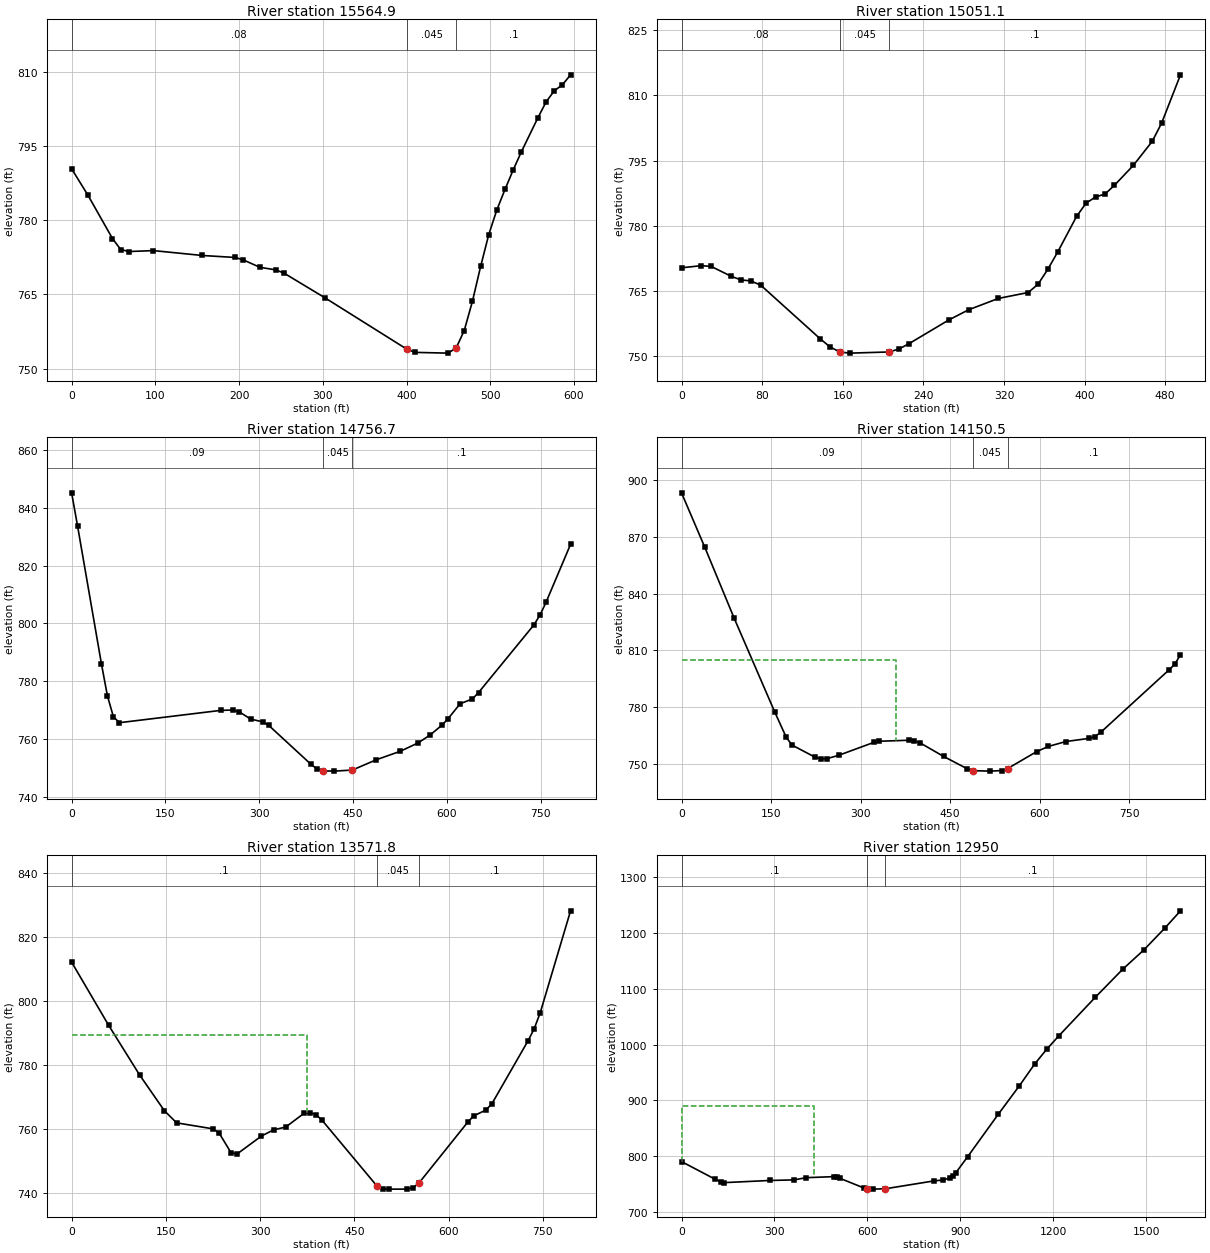
Type RM Length L Ch R = 1 ,15564.9 ,519.7,513.7,507.9
XS GIS Cut Line= 2
     1855733.152      399585.315     1856282.331      399353.957
#Sta/Elev= 30
       0  790.38    19.5  785.04    48.8  776.28    58.6  774.06    68.4  773.65
    97.7  773.84   156.3  772.85   195.4  772.45   205.2  771.95   224.7  770.47
   244.2  769.93     254  769.25   302.8  764.27   400.5  753.89   410.3  753.26
   449.4  753.11   459.2  754.13   468.9  757.67   478.7  763.58   488.5  770.65
   498.2  777.08     508  782.14   517.8   786.3   527.5   790.2   537.3  793.87
   556.8  800.67   566.6  803.88   576.4  806.15   586.2  807.37   595.9  809.38
#Mann= 3 , 0 , 0
       0     .08       0   400.5    .045       0   459.2      .1       0
Bank Sta=400.5,459.2
XS Rating Curve= 0 ,0
Exp/Cntr=0.3,0.1

Type RM Length L Ch R = 1 ,15051.1 ,296.1,294.4,292.9
XS GIS Cut Line= 3
     1856185.977      399994.582     1856482.852      399768.019
     1856563.581      399676.874
#Sta/Elev= 30
       0  770.27    19.7  770.76    29.5  770.58    49.1  768.33      59  767.48
    68.8  767.24    78.6  766.27   137.6  753.91   147.4  752.03   157.2  750.85
   167.1   750.6   206.4  750.87   216.2   751.6     226  752.81   265.4  758.26
     285   760.6   314.5  763.21     344  764.57   353.8  766.46   363.6  769.94
   373.4  773.93   392.2  782.16   401.6  785.19   410.9  786.59   420.3  787.27
   429.6  789.27   448.4  793.87   467.1  799.39   476.5  803.62   495.2  814.75
#Mann= 3 , 0 , 0
       0     .08       0   157.2    .045       0   206.4      .1       0
Bank Sta=157.2,206.4
XS Rating Curve= 0 ,0
Exp/Cntr=0.3,0.1

Type RM Length L Ch R = 1 ,14756.7 ,614.2,606.2,598.2
XS GIS Cut Line= 4
     1856243.269      400366.978     1856472.435      400150.832
     1856701.602      399947.707     1856808.373      399807.082
#Sta/Elev= 30
       0  845.13     9.6  833.56    47.7  786.01    57.3  774.93    66.8  767.77
    76.4  765.71   238.6  769.97   257.7  770.08   267.3  769.57   286.4  766.94
   305.5  766.01     315  764.82     382  751.48   391.6  749.83   401.2  749.08
   420.3  748.98     449  749.36   487.3  752.92   525.6  755.84   554.3  758.76
   573.4  761.49   592.5  764.92   602.1  767.14   621.2  772.25   640.9  773.94
   650.7  776.14     739  799.45   748.8  802.83   758.6  807.33   797.8  827.34
#Mann= 3 , 0 , 0
       0     .09       0   401.2    .045       0     449      .1       0
Bank Sta=401.2,449
XS Rating Curve= 0 ,0
Exp/Cntr=0.3,0.1

Type RM Length L Ch R = 1 ,14150.5 ,579.9,578.7,577.3
XS GIS Cut Line= 3
     1856852.644      400794.061     1857188.581      400166.457
     1857235.456      400051.874
#Sta/Elev= 30
       0  893.22      39  864.45    87.8  827.27     156  777.53   175.5     764
   185.3  759.91   224.3  753.45     234   752.7   243.8  752.79   263.3  754.55
   321.8  761.34   331.6  761.98   380.3   762.5   390.1  762.18   399.8  761.07
   438.8  753.99   477.8  747.55   487.6  746.45   516.8  746.19   536.3  746.48
   546.1  747.53   594.8  756.49   614.3  759.22   643.6  761.82   682.6  763.49
   692.4  764.46   702.1  766.68   816.6   799.7   826.1  802.65   835.7  807.66
#Mann= 3 , 0 , 0
       0     .09       0   487.6    .045       0   546.1      .1       0
#XS Ineff= 2 , 0
          359.61  804.69
Permanent Ineff=
       F       F
Bank Sta=487.6,546.1
XS Rating Curve= 0 ,0
Exp/Cntr=0.3,0.1

Type RM Length L Ch R = 1 ,13571.8 ,619.5,621.8,624
XS GIS Cut Line= 4
     1857352.644      400965.936     1857482.852      400877.394
     1857685.977      400439.894     1857717.227      400288.853
#Sta/Elev= 30
       0  812.16      59  792.42   108.2  776.95   147.6  765.79   167.1  761.99
     225  760.12   234.6  758.85   253.9  752.62   263.6  752.31   302.2  757.89
   321.5   759.8   340.8  760.68   369.7  764.94   379.3  765.19     389  764.53
   398.6   762.8   485.5  742.38   495.1  741.36   504.8   741.3   533.7   741.3
   543.3  741.69     553  743.25   630.2  762.15   639.8  764.15   659.1  765.97
   668.7  767.89   726.6  787.67   736.2  791.37   745.9  796.42   794.1  828.18
#Mann= 3 , 0 , 0
       0      .1       0   485.5    .045       0     553      .1       0
#XS Ineff= 2 , 0
          374.14  789.36
Permanent Ineff=
       F       F
Bank Sta=485.5,553
XS Rating Curve= 0 ,0
Exp/Cntr=0.3,0.1

Type RM Length L Ch R = 1 ,12950   ,476.7,487.9,499.1
XS GIS Cut Line= 4
     1857725.039      401413.853     1857912.539      401288.853
     1858253.685      400713.332     1858566.891      400069.777
#Sta/Elev= 30
       0  790.45   107.8  759.02   127.4  754.06   137.2  752.74   284.4  756.62
   363.1  757.65   402.4  761.65     491  763.46   500.8  762.59   510.7  760.59
   589.4  742.96   599.2  741.56   618.9   741.1   658.2  741.79   815.7  755.92
   845.2  757.52   864.9  760.82   874.7   764.1   884.5  769.92   923.8  799.51
  1021.8  875.02  1090.5  926.43  1139.5  965.25  1178.7  991.91  1217.9 1015.96
  1335.6  1085.1  1423.8 1135.16  1492.4 1169.97  1561.1 1209.68  1610.1 1239.81
#Mann= 3 , 0 , 0
       0      .1       0   599.2    .045       0   658.2      .1       0
#XS Ineff= 2 , 0
          427.28  890.56
Permanent Ineff=
       F       F
Bank Sta=599.2,658.2
XS Rating Curve= 0 ,0
Exp/Cntr=0.3,0.1

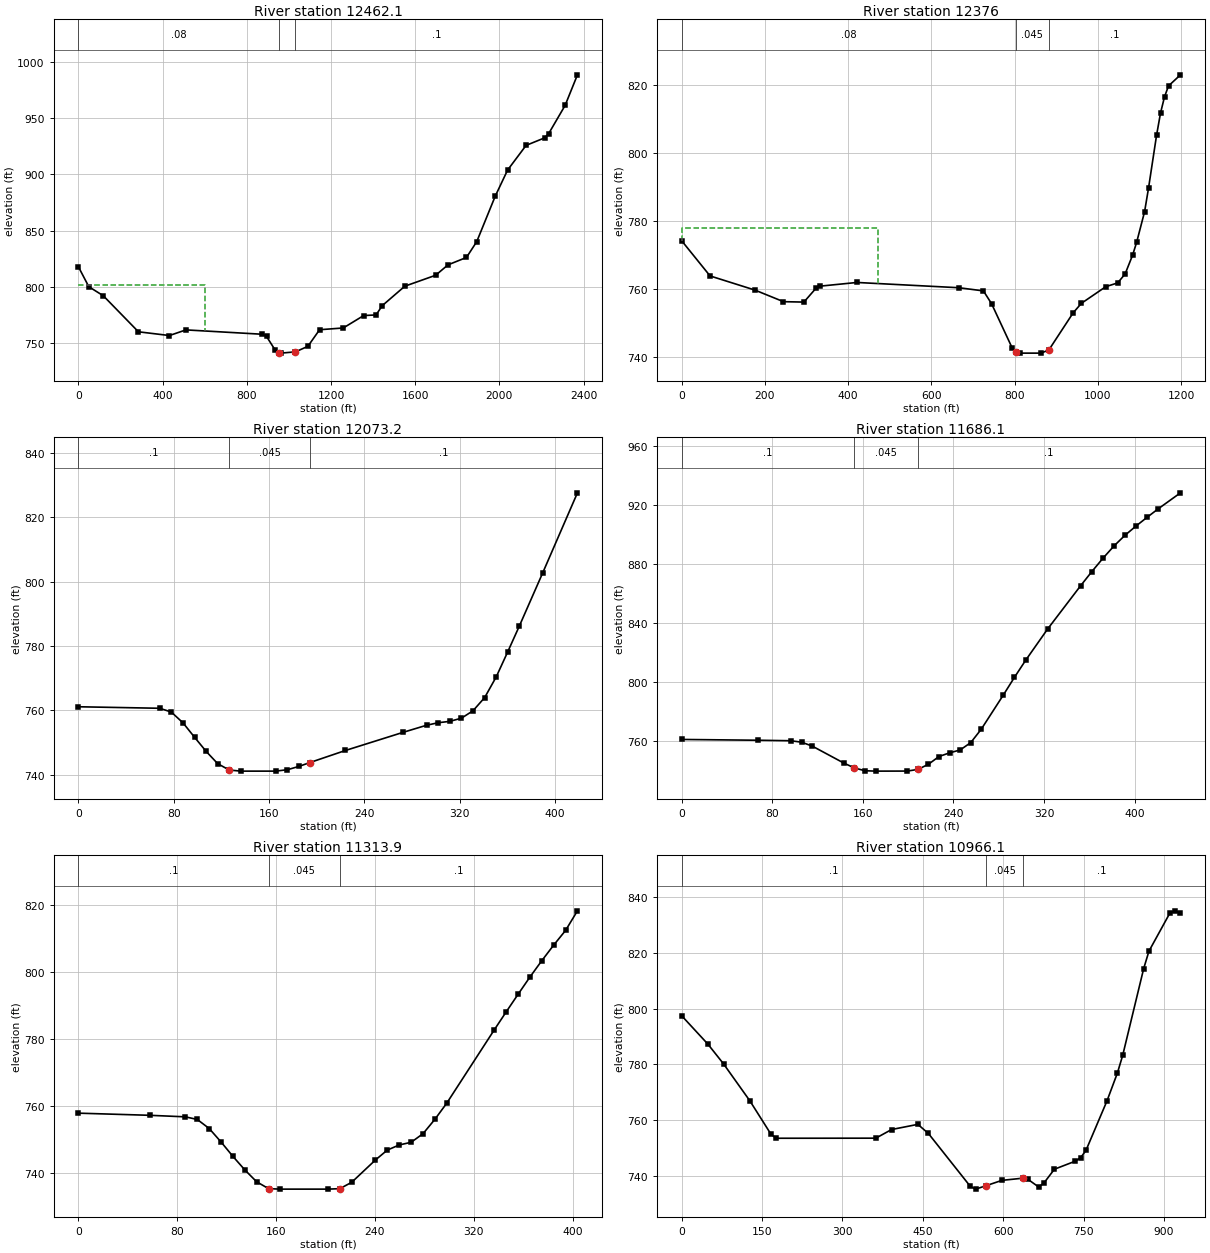
Type RM Length L Ch R = 1 ,12462.1 ,87.1,86,85
XS GIS Cut Line= 5
     1857681.474      401706.062     1858640.675      401128.805
     1858701.439      401122.295      1858866.37      401126.635
     1859851.613      400842.347
#Sta/Elev= 30
       0  817.66    49.1  800.09   117.8  792.08   284.8  760.05   432.1  756.73
   510.6  761.74     874  757.86   893.6  755.89   932.9  744.32   952.6  741.15
   962.4   741.1  1031.1  742.24    1090  747.13  1145.7  761.89  1258.3  763.45
  1355.4  774.49    1414  775.01  1443.3  783.24  1550.7  800.55  1697.2  810.27
  1755.8   819.5  1843.7   826.1  1892.5  840.14  1980.4  880.53    2039  903.68
  2126.9  925.62  2214.8  932.29  2234.3  936.09  2312.4  961.13    2371  988.31
#Mann= 3 , 0 , 0
       0     .08       0   952.6    .045       0  1031.1      .1       0
#XS Ineff= 2 , 0
           602.3   801.4
Permanent Ineff=
       F       F
Bank Sta=952.6,1031.1
XS Rating Curve= 0 ,0
Exp/Cntr=0.3,0.1

Type RM Length L Ch R = 1 ,12376   ,289.1,302.8,316.5
XS GIS Cut Line= 4
     1857842.064      401736.444      1858714.46      401172.208
     1858757.863      401183.058     1858851.179      401250.333
#Sta/Elev= 30
       0   774.2    68.6   763.8   176.4  759.64     245  756.23     294  756.11
   323.4  760.23   333.2   760.8   421.5  761.88   666.5  760.33   725.3   759.4
   744.9  755.63   793.9  742.75   803.7  741.37   813.5   741.1   862.5   741.1
   882.1  741.95   940.9  752.95   960.6  755.74  1019.4  760.65  1047.9  761.75
  1065.8   764.4  1083.7  769.92  1093.3  773.64  1112.5   782.7    1122  789.65
  1141.2  805.12  1150.8  811.72  1160.4  816.48    1170  819.68  1198.7  822.94
#Mann= 3 , 0 , 0
       0     .08       0   803.7    .045       0   882.1      .1       0
#XS Ineff= 2 , 0
          470.86  777.88
Permanent Ineff=
       F       F
Bank Sta=803.7,882.1
XS Rating Curve= 0 ,0
Exp/Cntr=0.3,0.1

Type RM Length L Ch R = 1 ,12073.2 ,375.4,387.2,398.9
XS GIS Cut Line= 2
      1858404.13      401580.194     1858822.967      401586.704
#Sta/Elev= 26
       0  761.11    68.2  760.64    77.9  759.47    87.7  756.13    97.4  751.65
   107.2  747.23   116.9  743.41   126.6  741.44   136.4   741.1   165.6   741.1
   175.4  741.54   185.1  742.57   194.3  743.77   224.1  747.52   272.8  753.19
   292.2  755.36     302  756.15   311.7  756.57   321.5  757.56   331.2  759.86
     341  763.96   350.7  770.39   360.4  778.21   370.2  786.27   389.7   802.7
   418.9  827.62
#Mann= 3 , 0 , 0
       0      .1       0   126.6    .045       0   194.3      .1       0
Bank Sta=126.6,194.3
XS Rating Curve= 0 ,0
Exp/Cntr=0.3,0.1

Type RM Length L Ch R = 1 ,11686.1 ,359.8,372.2,384.6
XS GIS Cut Line= 4
     1858414.981      401868.822     1858506.127      401923.076
     1858642.845      402003.371     1858803.436      402074.986
#Sta/Elev= 30
       0     761    67.5  760.46    96.4  760.13   106.1  759.13   115.4  756.49
   143.4  744.93   152.7  741.64     162  739.76   171.4   739.5   199.3  739.54
   208.7  740.66     218  744.16   227.3  749.42   236.6  751.89     246  753.87
   255.3  758.82   264.6  767.92   284.2  791.26   293.9  803.12   303.7   814.6
   323.2  835.94   352.5  865.47   362.3  874.97   372.1     884   381.8   892.3
   391.6  899.62   401.4  905.93   411.2  911.86   420.9  917.55   440.5  928.38
#Mann= 3 , 0 , 0
       0      .1       0   152.7    .045       0   208.7      .1       0
Bank Sta=152.7,208.7
XS Rating Curve= 0 ,0
Exp/Cntr=0.3,0.1

Type RM Length L Ch R = 1 ,11313.9 ,349.6,347.8,345.9
XS GIS Cut Line= 2
       1858239.2      402068.475     1858430.172      402424.378
#Sta/Elev= 29
       0  757.78    57.7  757.14    86.6  756.68    96.2  755.89   105.8   753.2
   115.4  749.18     125  744.88   134.6  740.86   144.2   737.3   153.9  735.24
   163.5   735.1     202   735.1   211.6  735.24   221.2  737.15   240.4  743.81
     250  746.76   259.6  748.28   269.3  749.09   278.9  751.65   288.5  755.94
   298.1  760.76   336.6  782.67   346.2  788.01   355.8  793.25   365.4   798.4
     375  803.28   384.7  807.97   394.3  812.34   403.9  818.19
#Mann= 3 , 0 , 0
       0      .1       0   153.9    .045       0   211.6      .1       0
Bank Sta=153.9,211.6
XS Rating Curve= 0 ,0
Exp/Cntr=0.3,0.1

Type RM Length L Ch R = 1 ,10966.1 ,490.2,488.3,486.5
XS GIS Cut Line= 2
     1857703.175      401905.715     1858208.818      402686.965
#Sta/Elev= 30
       0  797.47      49  787.26    78.4  780.13   127.4  766.88   166.5  754.97
   176.3  753.42   362.4  753.45   391.8  756.55   440.8  758.41   460.4  755.15
   538.8   736.1   548.6  735.15   568.2  736.39   597.6   738.3   636.7  739.08
   646.5  738.62   666.1  735.92   675.9  737.34   695.5   742.3   734.7  745.21
   744.5  746.47   754.3  749.04   793.5  766.81     813  776.87   822.8  783.15
     862  814.36   871.8   820.6     911  834.34   920.8  835.09   930.6  834.14
#Mann= 3 , 0 , 0
       0      .1       0   568.2    .045       0   636.7      .1       0
Bank Sta=568.2,636.7
XS Rating Curve= 0 ,0
Exp/Cntr=0.3,0.1

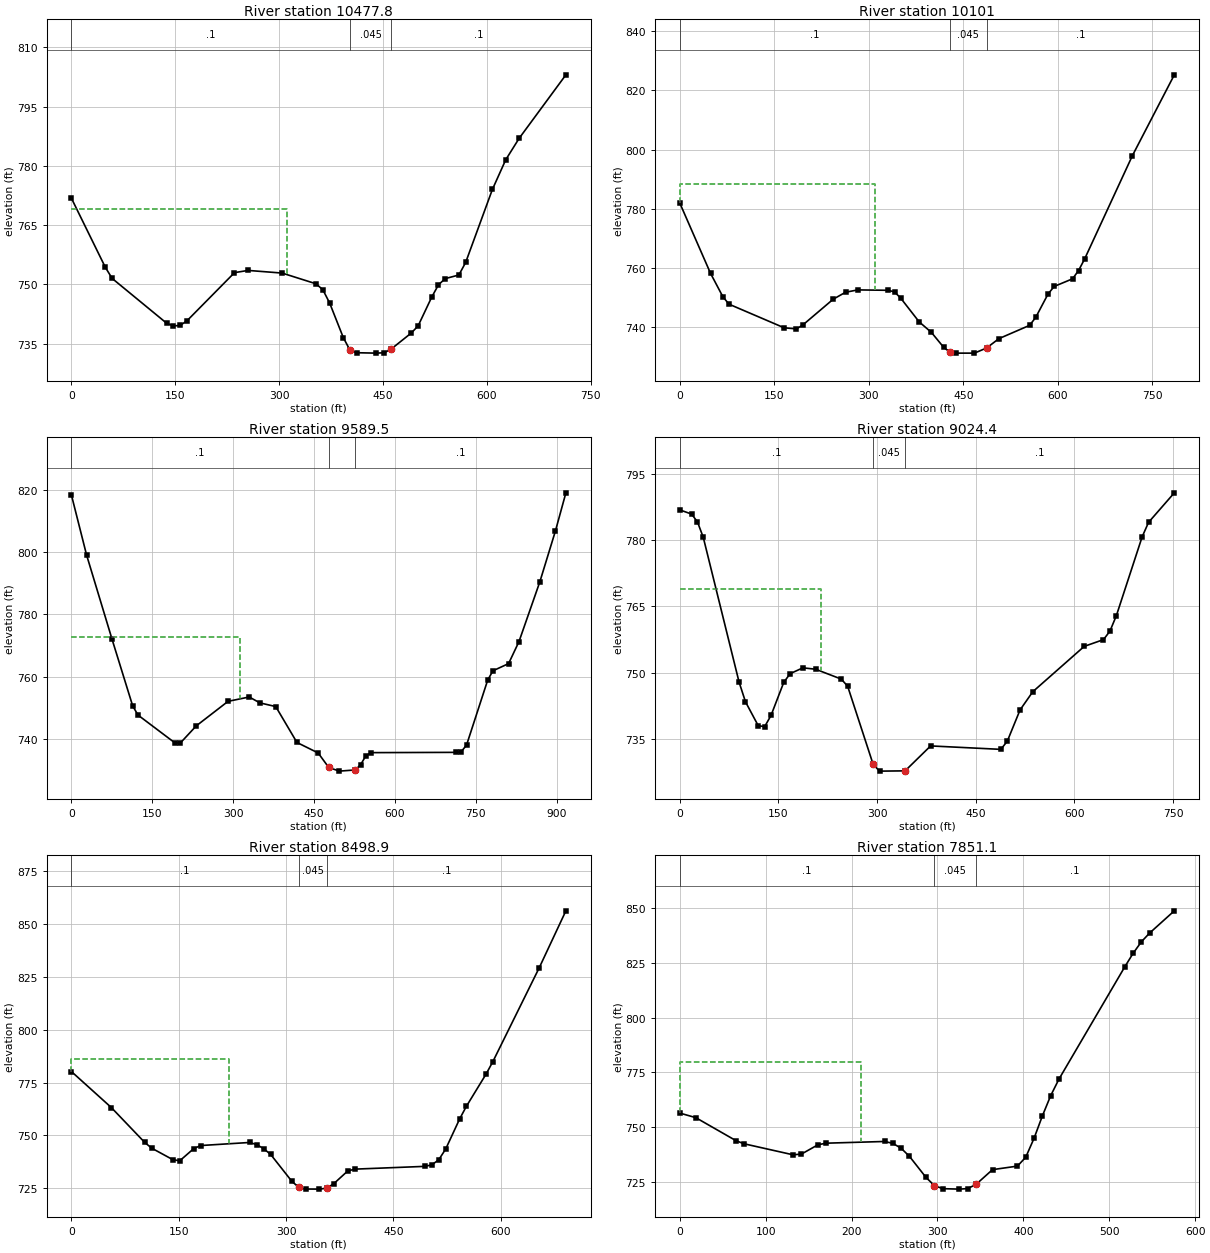
Type RM Length L Ch R = 1 ,10477.8 ,377.4,376.8,376.2
XS GIS Cut Line= 3
     1857401.526      402387.486     1857748.748      402838.874
     1857796.491      402975.593
#Sta/Elev= 30
       0  771.84    49.1  754.32    58.9  751.53   137.5  740.21   147.3   739.5
   157.1  739.65   166.9   740.8   235.6     753   255.3  753.56   304.4  752.89
   353.5  750.17   363.3  748.65   373.1  745.29   392.8  736.55   402.6  733.32
   412.4  732.73   439.8  732.63   451.7  732.72   461.5   733.6   490.9  737.71
   500.8  739.51   520.4  746.77   530.2  749.91     540  751.49   559.7   752.4
   569.5  755.57   608.1  774.04   627.4  781.56   646.7  786.97   714.3  803.06
#Mann= 3 , 0 , 0
       0      .1       0   402.6    .045       0   461.5      .1       0
#XS Ineff= 2 , 0
          311.07  769.18
Permanent Ineff=
       F       F
Bank Sta=402.6,461.5
XS Rating Curve= 0 ,0
Exp/Cntr=0.3,0.1

Type RM Length L Ch R = 1 ,10101   ,516,511.5,507
XS GIS Cut Line= 3
     1857106.387      402637.052     1857499.182      403120.992
     1857638.071      403203.458
#Sta/Elev= 30
       0  781.87    48.7  758.12    68.2  750.24    77.9  747.68   165.6  739.67
     185  739.31   194.8  740.55   243.5  749.36     263   751.7   282.4   752.5
   331.1  752.36   340.9  751.79   350.6   749.7   379.8   741.7   399.3  738.11
   418.8  733.05   428.5  731.46   438.2   731.1   467.5   731.1   486.9  732.84
   506.4     736   555.1   740.5   564.8  743.18   584.3  751.07   594.1  753.67
   623.3  756.25   632.8  759.05   642.3   762.9   718.3  797.95   784.8  825.29
#Mann= 3 , 0 , 0
       0      .1       0   428.5    .045       0   486.9      .1       0
#XS Ineff= 2 , 0
          309.65  788.27
Permanent Ineff=
       F       F
Bank Sta=428.5,486.9
XS Rating Curve= 0 ,0
Exp/Cntr=0.3,0.1

Type RM Length L Ch R = 1 ,9589.5  ,573.5,565.1,556.7
XS GIS Cut Line= 4
     1856657.168       403086.27     1856746.144      403116.652
     1857269.147       403548.51     1857381.995      403639.656
#Sta/Elev= 30
       0  818.34    28.2  799.02    75.2  772.09   113.7  750.55   123.5  747.62
   192.3  738.64   202.2  738.65   231.6  744.13   290.6  752.02   329.9  753.42
   349.6  751.53   379.1  750.34   418.4  738.81   457.7  735.44   477.4  730.78
     497   729.6   526.5  729.98   536.4  731.63   546.2  734.51     556  735.54
   713.3  735.63   723.1  735.84     733  737.96   772.3  758.87     782  761.84
     811  764.14   830.3  771.22     869  790.43     898  806.82   917.3  819.01
#Mann= 3 , 0 , 0
       0      .1       0   477.4    .045       0   526.5      .1       0
#XS Ineff= 2 , 0
          312.67  772.81
Permanent Ineff=
       F       F
Bank Sta=477.4,526.5
XS Rating Curve= 0 ,0
Exp/Cntr=0.3,0.1

Type RM Length L Ch R = 1 ,9024.4  ,527.1,525.5,523.9
XS GIS Cut Line= 4
     1856496.144      403827.156     1856569.061      403793.302
     1857011.769      403939.135     1857188.852      403834.968
#Sta/Elev= 30
       0  786.87    17.9  785.93    26.8  784.16    35.7  780.63    90.1  747.87
    99.8  743.42   119.2     738     129  737.77   138.7  740.32   158.1  747.82
   167.8  749.78   187.2   751.1   206.6  750.78   245.5  748.55   255.2  746.94
     294  729.23   303.7   727.7   342.6  727.76   381.4  733.41   488.2  732.63
     498  734.48   517.4  741.56   536.8  745.69     615  755.96   644.3  757.49
   654.1  759.42   663.9  762.93     703  780.74   712.8  784.05     752  790.74
#Mann= 3 , 0 , 0
       0      .1       0     294    .045       0   342.6      .1       0
#XS Ineff= 2 , 0
          213.99  768.88
Permanent Ineff=
       F       F
Bank Sta=294,342.6
XS Rating Curve= 0 ,0
Exp/Cntr=0.3,0.1

Type RM Length L Ch R = 1 ,8498.9  ,649.1,647.8,646.5
XS GIS Cut Line= 4
     1856418.019      404347.989     1856519.581      404334.968
     1856946.665      404441.739     1857063.852      404532.885
#Sta/Elev= 30
       0  780.21    55.8   763.2   102.4  746.74   112.2  744.01   141.5  738.62
   151.3     738   170.9  743.76   180.7  745.24   249.1  746.69   258.9  745.68
   268.7  743.78   278.5  741.04   307.8  728.47   317.6  725.52   327.4   724.7
   346.5  724.65   356.8  725.08   366.5  727.16   386.1  733.19   395.9  734.09
   493.7   735.4   503.5  736.08   513.3  738.47   523.1  743.58   542.6   757.8
   551.9  763.69   579.7  779.08     589  784.86     654  829.34   691.1  856.12
#Mann= 3 , 0 , 0
       0      .1       0   317.6    .045       0   356.8      .1       0
#XS Ineff= 2 , 0
          220.11  785.89
Permanent Ineff=
       F       F
Bank Sta=317.6,356.8
XS Rating Curve= 0 ,0
Exp/Cntr=0.3,0.1

Type RM Length L Ch R = 1 ,7851.1  ,449.3,445,440.8
XS GIS Cut Line= 4
     1856384.165      404939.135     1856459.686      404993.822
     1856782.602      405056.322     1856936.248      405056.322
#Sta/Elev= 30
       0  756.38    18.6  754.29    65.3  743.79    74.6  742.36   131.9   737.3
   141.6  737.64     161  741.92   170.6  742.62   238.4   743.4     248  742.54
   257.7   740.3   267.4  736.59   286.7  726.94   296.4  723.25   306.1  721.82
   325.4  721.61   335.1  721.85   344.8  723.73   364.1  730.52   393.1  732.13
   402.8  736.19   412.5  744.89   422.2  755.12   431.8  764.31   441.4  771.86
   518.2   823.3   527.8  829.42   537.4  834.68     547  838.68   575.8  848.86
#Mann= 3 , 0 , 0
       0      .1       0   296.4    .045       0   344.8      .1       0
#XS Ineff= 2 , 0
          211.51  779.64
Permanent Ineff=
       F       F
Bank Sta=296.4,344.8
XS Rating Curve= 0 ,0
Exp/Cntr=0.3,0.1

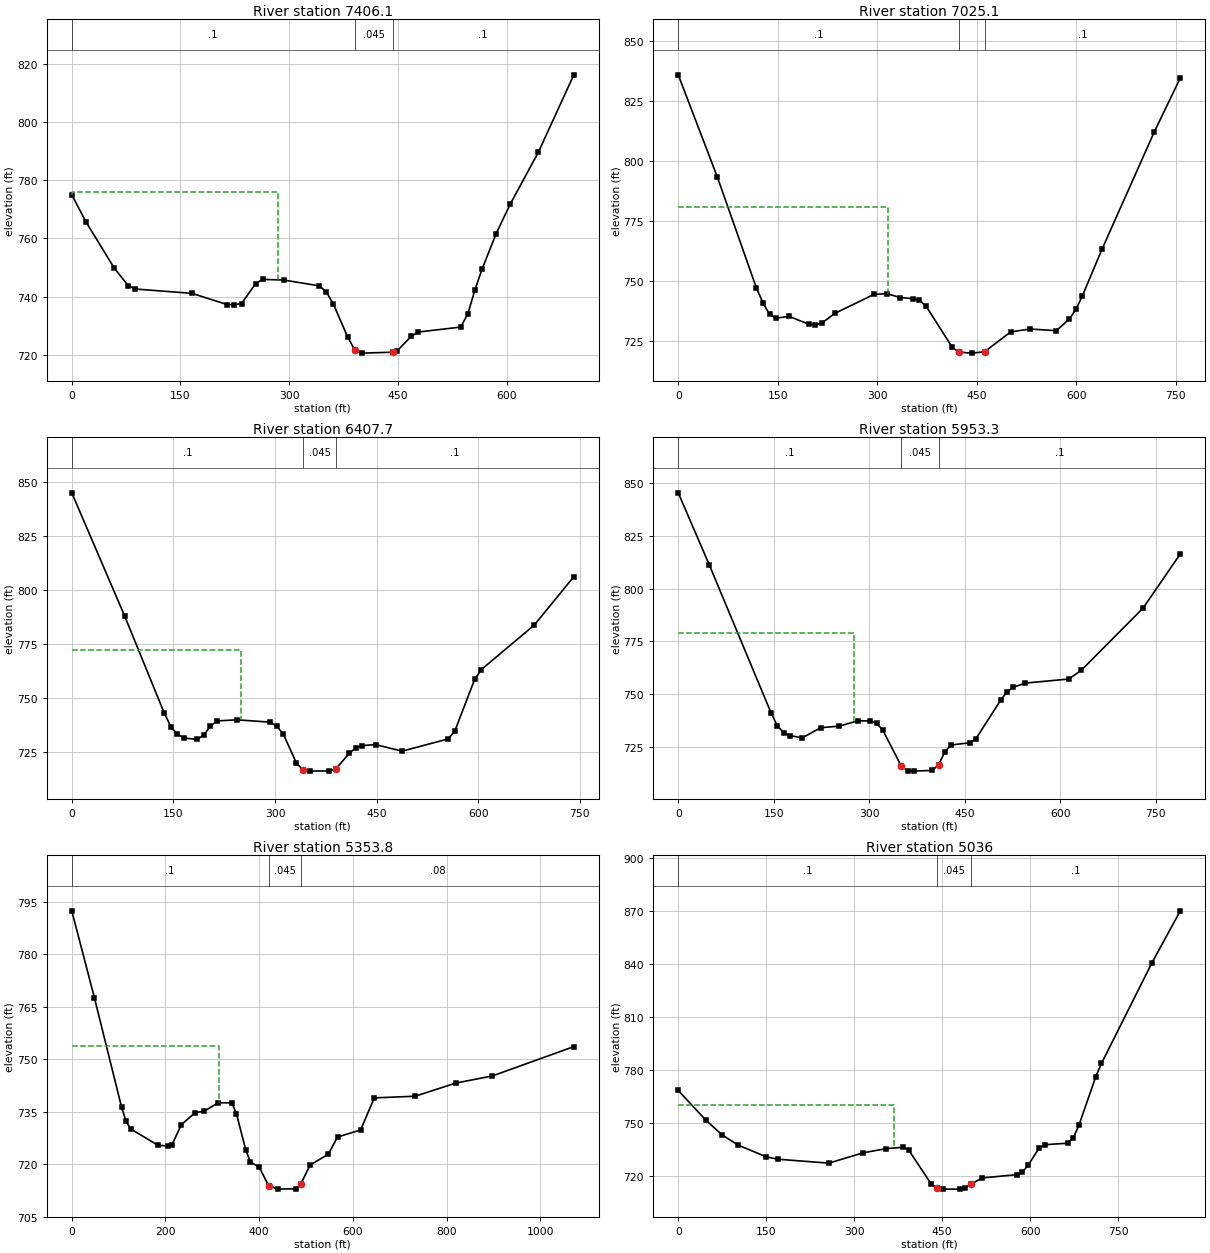
Type RM Length L Ch R = 1 ,7406.1  ,390.6,381,371.5
XS GIS Cut Line= 2
     1856233.123      405478.197     1856925.831      405480.802
#Sta/Elev= 30
       0  774.98    19.5  765.68    58.5  749.81      78  743.69    87.8  742.58
   165.9  741.08   214.6  737.23   224.4   737.2   234.2  737.57   253.7  744.46
   263.4  745.88   292.7  745.66   341.5  743.66   351.2   741.6     361  737.37
   380.5  726.16   390.3  721.65     400  720.55   442.7  720.86   448.8  721.28
   468.3  726.31   478.1   727.8   536.6   729.5   546.4  734.01   556.1   742.2
   565.9  749.31   585.4  761.55   604.9  771.73   643.9  789.66   692.7  816.17
#Mann= 3 , 0 , 0
       0      .1       0   390.3    .045       0   442.7      .1       0
#XS Ineff= 2 , 0
          283.97  775.87
Permanent Ineff=
       F       F
Bank Sta=390.3,442.7
XS Rating Curve= 0 ,0
Exp/Cntr=0.3,0.1

Type RM Length L Ch R = 1 ,7025.1  ,618.9,617.3,615.7
XS GIS Cut Line= 2
     1856293.019      406038.093     1856985.727      405733.406
#Sta/Elev= 30
       0  835.87      59  793.31   117.9  747.14   127.8  740.96   137.6  736.23
   147.4  734.62   167.1  735.39   196.6  732.13   206.4  731.83   216.2  732.52
   235.9   736.6   294.8  744.48   314.5  744.85   334.2  743.22   353.8  742.74
   363.6  742.01   373.5  739.66   412.8  722.61   422.6  720.52   442.3  720.08
   461.9  720.67   501.2  728.94   530.7  730.11     570  729.42   589.7  734.33
   599.5  738.29   609.3  743.99   638.8  763.34   717.4  812.02   756.8  834.58
#Mann= 3 , 0 , 0
       0      .1       0   422.6    .045       0   461.9      .1       0
#XS Ineff= 2 , 0
          316.03  780.77
Permanent Ineff=
       F       F
Bank Sta=422.6,461.9
XS Rating Curve= 0 ,0
Exp/Cntr=0.3,0.1

Type RM Length L Ch R = 1 ,6407.7  ,453.9,454.4,454.9
XS GIS Cut Line= 2
     1856605.519      406600.593     1857259.165      406251.635
#Sta/Elev= 30
       0  845.05      78  788.08   136.5  743.13   146.2  736.83     156  733.28
   165.7  731.57   185.2  730.91     195  733.02   204.7   737.1   214.5  739.49
   243.7     740   292.5  738.92   302.2  737.11     312  733.55   331.5  720.03
   341.2  716.87     351  716.25   380.2  716.37     390  717.34   409.5  724.49
   419.2  727.04     429  728.09   448.5  728.52   487.5  725.49   555.7  731.16
   565.5  734.92   594.7   758.8   604.5  763.27   682.5  783.81     741  806.26
#Mann= 3 , 0 , 0
       0      .1       0   341.2    .045       0     390      .1       0
#XS Ineff= 2 , 0
          250.13  772.45
Permanent Ineff=
       F       F
Bank Sta=341.2,390
XS Rating Curve= 0 ,0
Exp/Cntr=0.3,0.1

Type RM Length L Ch R = 1 ,5953.3  ,591.3,599.5,607.7
XS GIS Cut Line= 2
     1856811.248      406996.427     1857514.373      406639.656
#Sta/Elev= 30
       0  845.46    48.7  811.35     146  740.96   155.8  734.94   165.5   731.8
   175.2  730.36   194.7  729.28   223.9  734.09   253.1  734.86   282.3  737.37
   301.8  737.29   311.5  736.14   321.2  732.99   350.4  715.81   360.2  713.79
   369.9   713.5   399.1  713.85   408.8  716.46   418.6  722.57   428.3  725.89
   457.5  726.92   467.2  728.74   506.2  747.05   515.9  750.94   525.6  753.21
   545.1  755.24   613.2  757.17   632.7  761.22   730.1  790.82   788.5  816.51
#Mann= 3 , 0 , 0
       0      .1       0   350.4    .045       0   408.8      .1       0
#XS Ineff= 2 , 0
          275.64  779.18
Permanent Ineff=
       F       F
Bank Sta=350.4,408.8
XS Rating Curve= 0 ,0
Exp/Cntr=0.3,0.1

Type RM Length L Ch R = 1 ,5353.8  ,315.3,317.8,320.3
XS GIS Cut Line= 4
     1856944.061      407389.656     1857048.227      407410.489
     1857584.686      407353.197     1857975.311      407183.927
#Sta/Elev= 30
       0  792.48    48.3  767.63   106.2  736.38     116  732.25   125.8  730.11
   184.7  725.38   204.3  725.31   214.1  725.65   233.8  731.33   263.2  734.76
   282.8   735.2   312.2  737.58   341.6  737.58   351.5  734.42   371.1  724.23
   380.9   720.7   400.5   719.1   420.1  713.81   439.7   712.9     479  713.01
   488.8  714.37   508.4  719.76   547.6   722.9   567.3  727.81   616.3   729.8
   645.7  738.99   732.8  739.47   819.9  743.24   897.3  745.25  1071.5  753.65
#Mann= 3 , 0 , 0
       0      .1       0   420.1    .045       0   488.8     .08       0
#XS Ineff= 2 , 0
          314.61   753.7
Permanent Ineff=
       F       F
Bank Sta=420.1,488.8
XS Rating Curve= 0 ,0
Exp/Cntr=0.3,0.1

Type RM Length L Ch R = 1 ,5036    ,734.7,742.5,750.3
XS GIS Cut Line= 4
     1856938.852      407738.614     1857058.644      407686.531
     1857553.436      407686.531     1857777.394      407741.218
#Sta/Elev= 30
       0  768.57    46.6  751.95    74.6  743.45   102.6  737.56     150  731.01
   169.4  729.65   256.8  727.43     315  733.26   353.8   735.6   382.9  736.41
   392.6  735.02   431.4  715.52   441.1  713.14   450.8   712.7   479.9   712.7
   489.6  713.52   499.3  715.56   518.7  719.08   576.9  720.87   586.6  722.29
   596.3  726.11   615.7  736.16   625.4  737.88   663.8   738.7   673.4  741.61
     683  748.75   711.9  776.44   721.5  783.87   807.9  841.06     856  870.34
#Mann= 3 , 0 , 0
       0      .1       0   441.1    .045       0   499.3      .1       0
#XS Ineff= 2 , 0
          367.58  760.38
Permanent Ineff=
       F       F
Bank Sta=441.1,499.3
XS Rating Curve= 0 ,0
Exp/Cntr=0.3,0.1

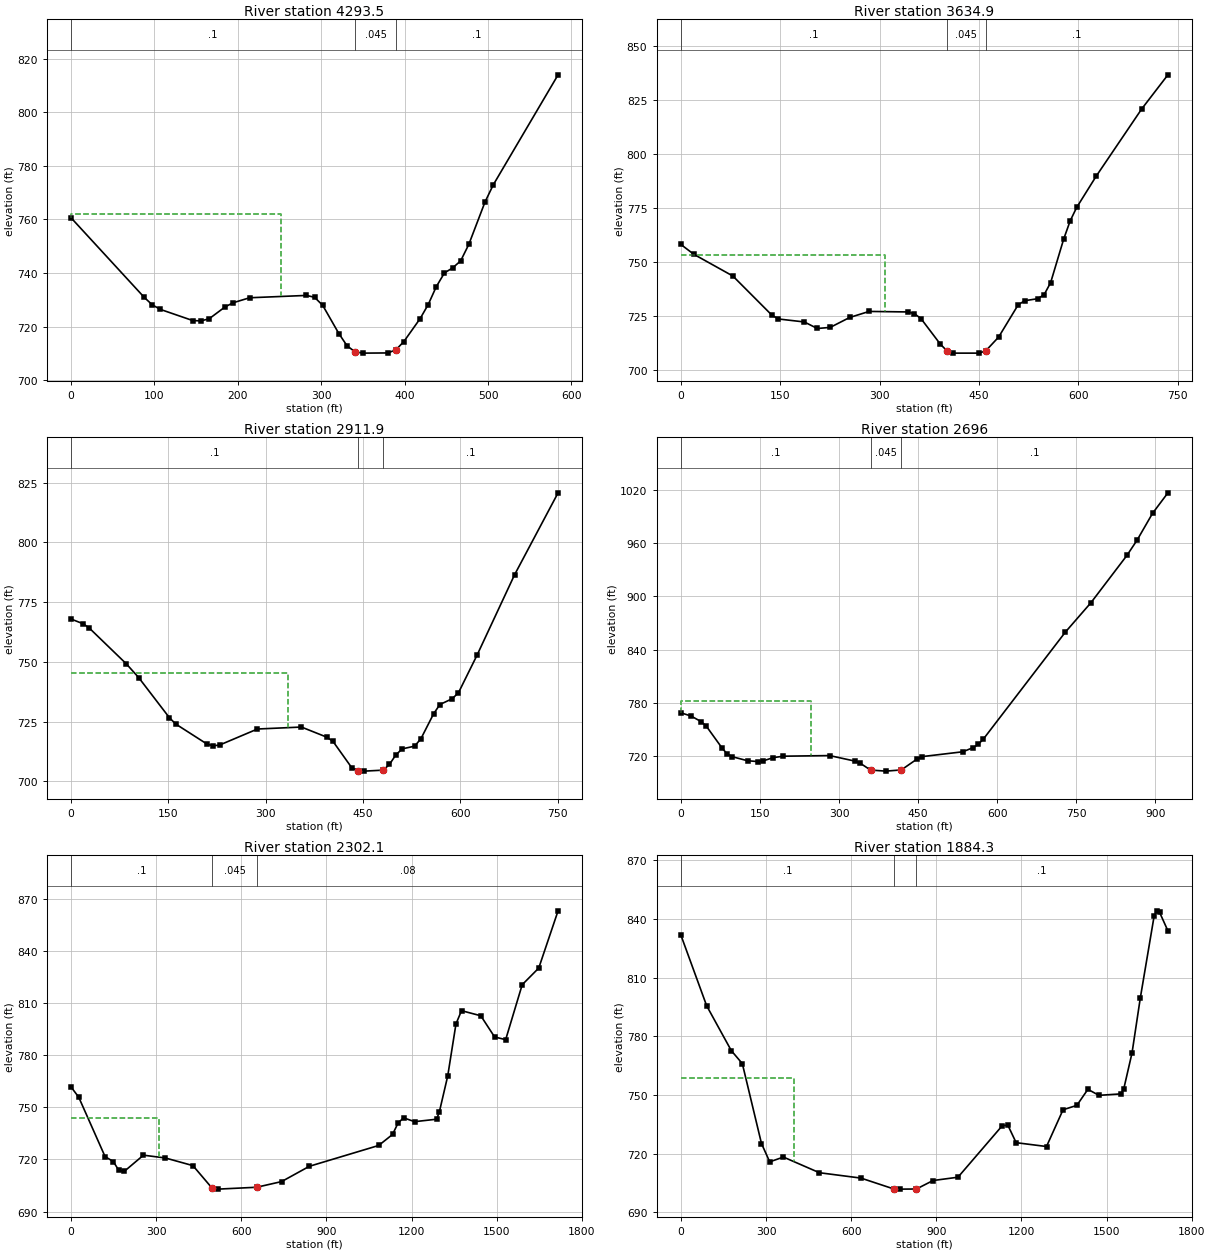
Type RM Length L Ch R = 1 ,4293.5  ,660.4,658.6,656.7
XS GIS Cut Line= 2
     1856959.686      408288.093     1857509.165       408486.01
#Sta/Elev= 30
       0  760.61    87.6  730.97    97.3  728.15   107.1  726.42     146  722.25
   155.7  722.13   165.5  722.89   184.9  727.39   194.7  728.93   214.2  730.76
   282.3  731.63     292  730.94   301.8  727.92   321.2  717.37     331  712.83
   340.7  710.54   350.4   710.1   379.6  710.17   389.4  711.28   399.1  714.42
   418.6  722.98   428.3  728.23     438  734.91   447.8  740.04   457.5  741.89
   467.2  744.52     477  750.69   496.4  766.49   506.2  772.84     584  813.94
#Mann= 3 , 0 , 0
       0      .1       0   340.7    .045       0   389.4      .1       0
#XS Ineff= 2 , 0
           251.9  762.14
Permanent Ineff=
       F       F
Bank Sta=340.7,389.4
XS Rating Curve= 0 ,0
Exp/Cntr=0.3,0.1

Type RM Length L Ch R = 1 ,3634.9  ,724.6,723,721.5
XS GIS Cut Line= 4
     1856756.561      408957.364     1856891.977      408980.802
     1857269.581      409082.364     1857475.311      409100.593
#Sta/Elev= 30
       0  758.08    19.6  753.51    78.5  743.44   137.4  725.29   147.2  723.53
   186.3  722.15   205.9  719.12   225.4  719.63   254.7  724.22   284.1  727.03
   342.7  726.79   352.5  725.98   362.3  723.73   391.6  711.85   401.4   708.8
   411.2   707.7   450.2   707.7     460  708.72   479.6  715.17   508.9  730.03
   518.7  731.99   538.3  732.92   548.1  734.75     558  740.37   577.6  760.46
   587.5  769.02   597.3  775.22   626.8  789.74   695.6  820.96     735  836.71
#Mann= 3 , 0 , 0
       0      .1       0   401.4    .045       0     460      .1       0
#XS Ineff= 2 , 0
          307.53  753.04
Permanent Ineff=
       F       F
Bank Sta=401.4,460
XS Rating Curve= 0 ,0
Exp/Cntr=0.3,0.1

Type RM Length L Ch R = 1 ,2911.9  ,213.5,215.9,218.2
XS GIS Cut Line= 4
     1856597.706      409722.989     1856748.748      409709.968
     1857157.602      409790.697     1857339.894      409790.697
#Sta/Elev= 30
       0  767.94      19  765.91    28.4  764.09    85.3  749.16   104.2  743.46
   151.6  726.66   161.3  724.02   209.8  715.58   219.4   714.9   229.1  715.23
   287.3  721.92   355.1  722.74   393.9  718.54   403.6  716.79   432.7   705.7
   442.4  704.46     452   704.3   481.1  704.71   490.8  707.13   500.5  711.05
   510.2  713.59   529.6  714.76   539.3  717.89   558.7  728.24   568.4  732.15
   587.5   734.6   597.1   737.1   625.9  752.91   683.5  786.42   750.6  820.73
#Mann= 3 , 0 , 0
       0      .1       0   442.4    .045       0   481.1      .1       0
#XS Ineff= 2 , 0
          335.16  745.54
Permanent Ineff=
       F       F
Bank Sta=442.4,481.1
XS Rating Curve= 0 ,0
Exp/Cntr=0.3,0.1

Type RM Length L Ch R = 1 ,2696    ,355.9,393.9,431.9
XS GIS Cut Line= 3
     1856639.373      409866.652     1857178.436      410033.319
     1857537.811      410048.944
#Sta/Elev= 30
       0  768.88    19.5  765.18    38.9   758.8    48.6  753.56    77.8  729.51
    87.6  722.61    97.3  719.47   126.5  714.88   145.9     714   155.6  714.62
   175.1  718.39   194.6  720.01   282.1  720.71   330.8  714.41   340.5     712
     360  704.38   389.1   703.2   418.3  704.56   447.5  716.59   457.2   719.5
     535     725   554.5  729.68   564.2  733.33     574  739.36   729.5  859.74
   778.1  892.89   846.2  945.99   865.6  963.31   894.8  993.36     924 1016.49
#Mann= 3 , 0 , 0
       0      .1       0     360    .045       0   418.3      .1       0
#XS Ineff= 2 , 0
          246.24  782.14
Permanent Ineff=
       F       F
Bank Sta=360,418.3
XS Rating Curve= 0 ,0
Exp/Cntr=0.3,0.1

Type RM Length L Ch R = 1 ,2302.1  ,415.9,417.8,433.7
XS GIS Cut Line= 6
     1856535.206      410098.423     1856615.936       410108.84
     1856904.998      410127.069      1856899.79      410752.069
     1856949.269      410879.673     1857532.602      410874.465
#Sta/Elev= 30
       0  761.81    27.1  755.91     120  721.66     149   718.8   168.3  713.75
   187.6  713.13   255.2  722.47   332.4  720.86   429.6  716.45     498   703.3
   517.5   702.9   654.2  703.98   742.1  707.25   839.8  716.06    1084  728.06
  1132.9   734.4  1152.4  740.98  1171.8  744.02  1210.7  741.79  1288.5  743.21
  1298.2   747.6  1327.4   768.1  1356.5  798.12    1376  805.78    1444  802.84
  1492.6  790.63  1531.6  789.06  1589.9  820.75  1648.2  830.34  1716.3  863.34
#Mann= 3 , 0 , 0
       0      .1       0     498    .045       0   654.2     .08       0
#XS Ineff= 2 , 0
          310.89  743.62
Permanent Ineff=
       F       F
Bank Sta=498,654.2
XS Rating Curve= 0 ,0
Exp/Cntr=0.3,0.1

Type RM Length L Ch R = 1 ,1884.3  ,353.8,320.7,274.2
XS GIS Cut Line= 6
     1856287.811      410226.027      1856368.54      410236.444
     1856657.602      410254.673     1856652.394      410879.673
     1856701.873      411007.277     1857285.206      411002.069
#Sta/Elev= 30
       0  831.84      91  795.63   177.9  772.69   216.6  766.09   284.1  725.22
   313.1  715.85   361.4   718.3   488.2  710.29   634.7  707.54   751.9  701.91
   771.4   701.9     830  701.96   888.6   706.3   976.5  707.99  1132.9   734.4
  1152.4  734.56  1181.5  725.65  1288.5  723.69  1346.8  742.49  1395.4  744.73
  1434.3  752.94  1473.2  749.86    1551  750.61  1560.7  753.17  1589.9  771.59
    1619  799.63  1667.7  841.52  1677.4  844.22  1687.1   843.4  1716.3  833.98
#Mann= 3 , 0 , 0
       0      .1       0   751.9    .045       0     830      .1       0
#XS Ineff= 2 , 0
          400.18  758.98
Permanent Ineff=
       F       F
Bank Sta=751.9,830
XS Rating Curve= 0 ,0
Exp/Cntr=0.3,0.1