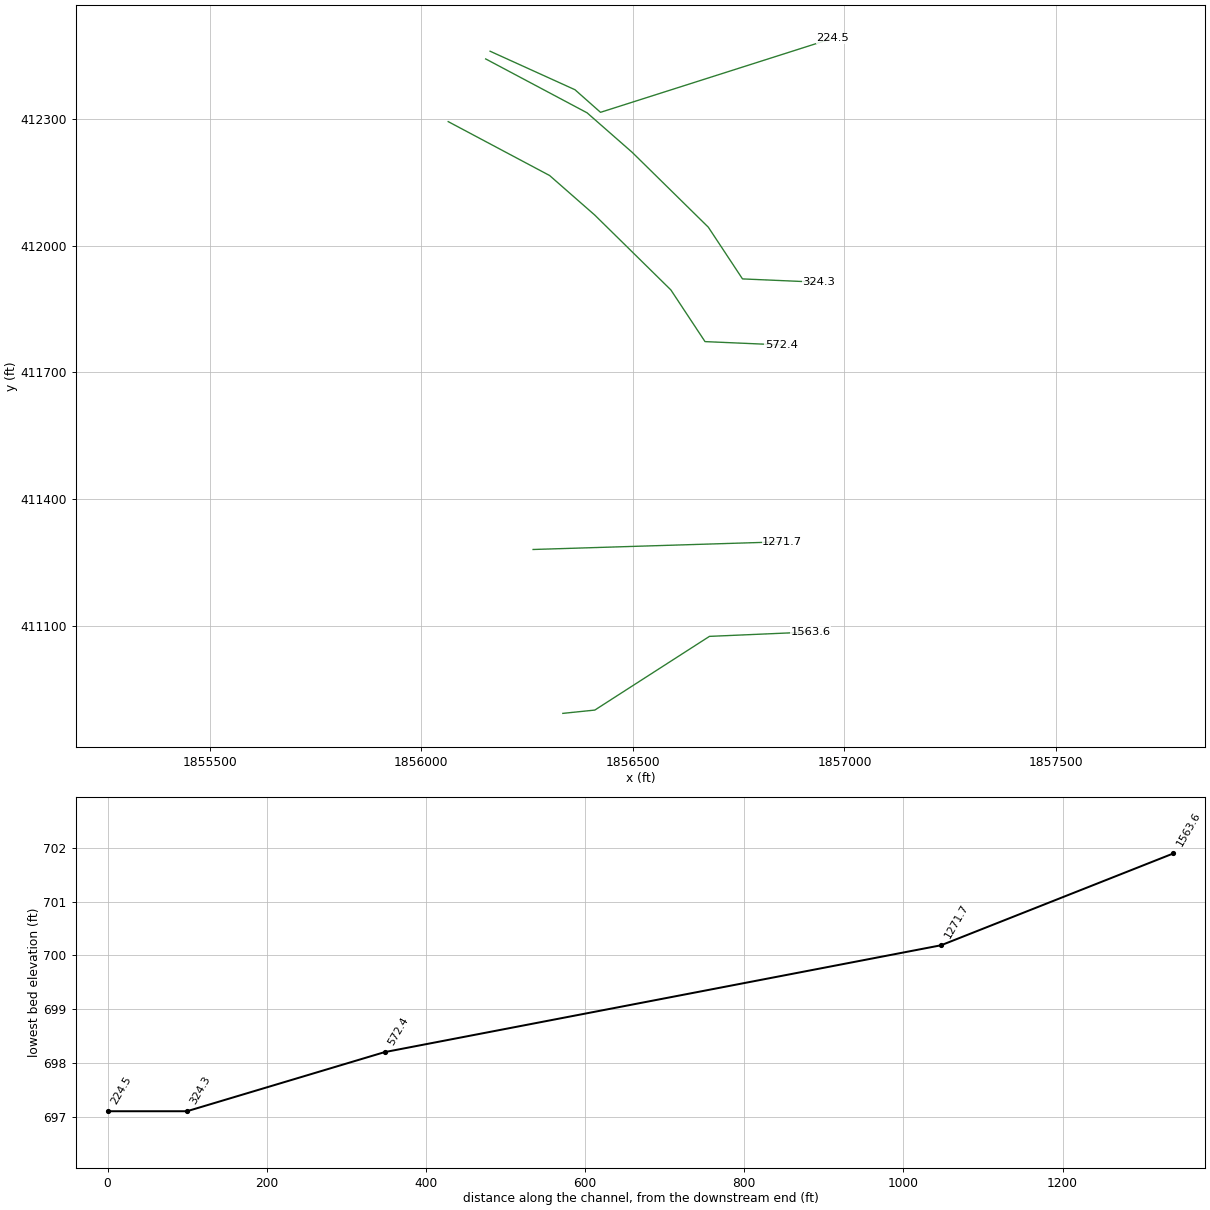
HEC-RAS study PAINTCK.prj: PAINTCK

--- PAINTCK.g01 (geometry) --- (continued)

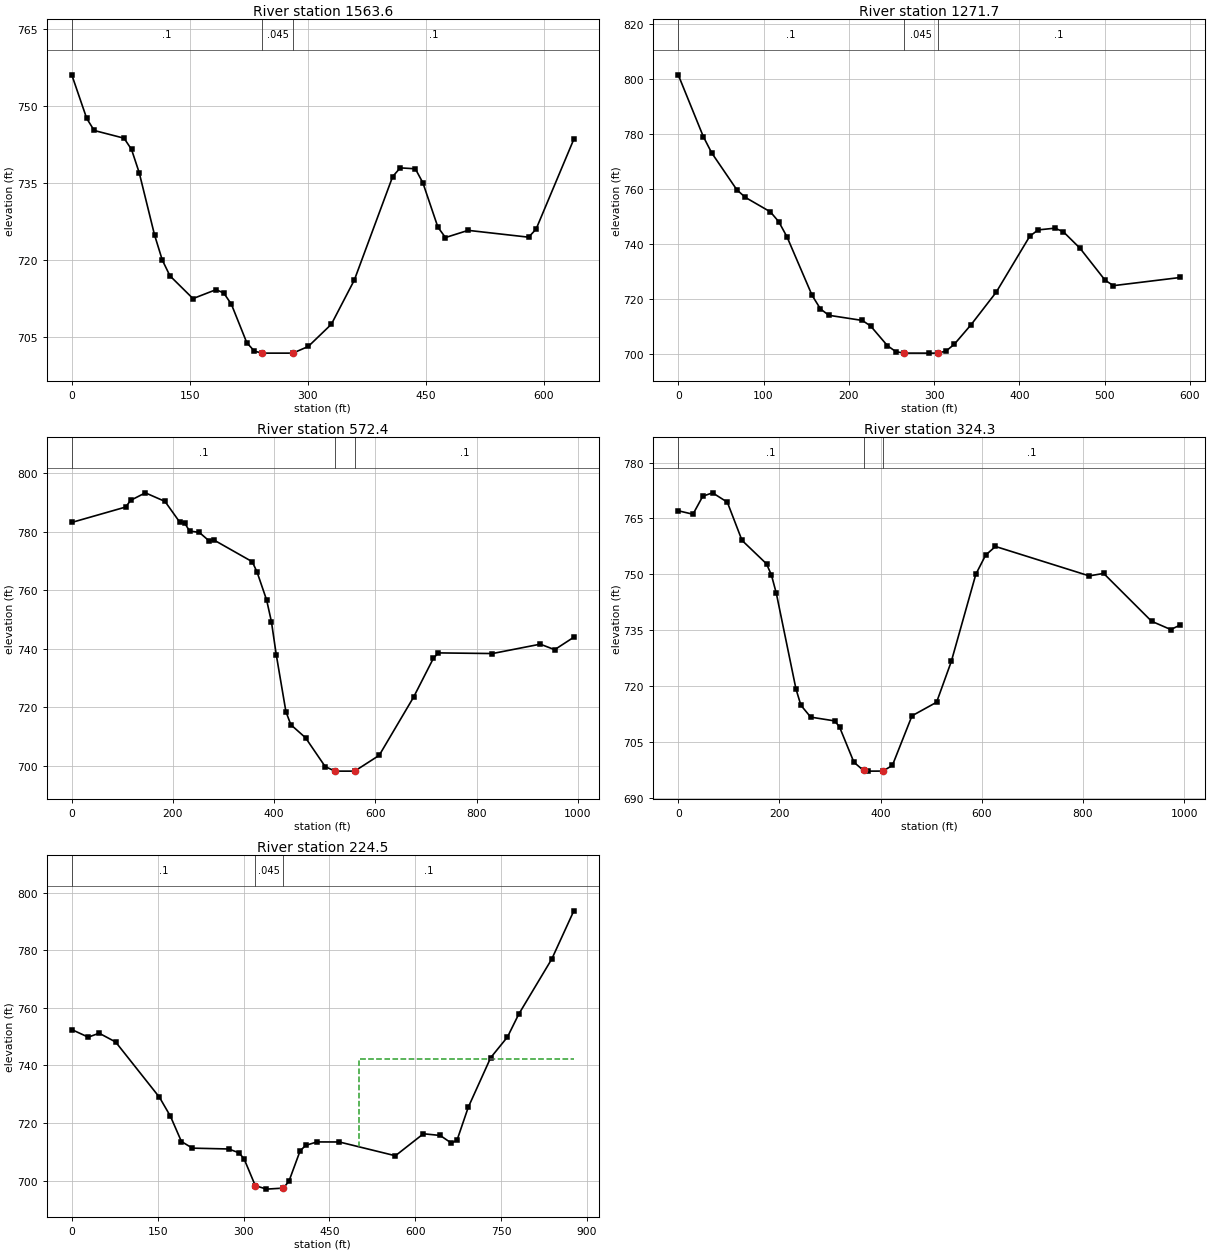
Type RM Length L Ch R = 1 ,1563.6  ,304.7,291.9,278.5
XS GIS Cut Line= 4
     1856334.686      410892.694     1856410.206      410900.506
      1856681.04      411074.986     1856920.623      411085.402
#Sta/Elev= 30
       0   756.1      19   747.6    28.5  745.26    66.4  743.76    75.9  741.58
    85.7  737.03   105.2  724.89     115  720.03   124.7  716.96     154  712.52
   183.3  714.26   193.1  713.61   202.8  711.42   222.4  703.92   232.1  702.28
   241.9   701.9   280.9   701.9   300.5   703.2   329.8  707.52     359  716.13
   407.7  736.28   417.3  737.98   436.5   737.8   446.1  735.07   465.2  726.42
   474.8  724.41   503.6  725.81   580.4  724.48   589.9  726.04   637.9  743.57
#Mann= 3 , 0 , 0
       0      .1       0   241.9    .045       0   280.9      .1       0
Bank Sta=241.9,280.9
XS Rating Curve= 0 ,0
Exp/Cntr=0.3,0.1

Type RM Length L Ch R = 1 ,1271.7  ,725,699.3,676.9
XS GIS Cut Line= 2
     1856264.373      411280.715     1856852.915      411298.944
#Sta/Elev= 30
       0  801.62    29.4  779.12    39.2  773.19    68.7  759.73    78.5  756.99
     108  751.69   117.8  748.13   127.6  742.53     157  721.23   166.8   716.3
   176.6  713.98   215.9   712.1   225.7  710.05   245.3  702.92   255.2  700.72
     265   700.2   293.6  700.19   304.2  700.19     314  700.92   323.8  703.44
   343.5  710.58   372.9   722.4   412.2  742.77     422   745.1   441.6  745.72
   451.4  744.49   471.1  738.44   500.5   726.8   510.3  724.78   588.8  727.76
#Mann= 3 , 0 , 0
       0      .1       0     265    .045       0   304.2      .1       0
Bank Sta=265,304.2
XS Rating Curve= 0 ,0
Exp/Cntr=0.3,0.1

Type RM Length L Ch R = 1 ,572.4   ,244.5,248.2,248
XS GIS Cut Line= 6
     1856063.852      412293.736     1856303.436      412166.131
     1856410.206      412072.381     1856589.894      411895.298
     1856670.623      411772.902     1856850.311       411765.09
#Sta/Elev= 30
       0  783.14   106.6   788.4   116.3  790.68   145.4  793.25   184.2  790.32
   213.3  783.26     223  782.97   232.7  780.22   252.1  779.72   271.4  776.84
   280.9  777.14   356.7  769.72   366.2  766.19   385.1  756.65   394.6  749.23
   404.1  738.02   423.2  718.55   432.9  714.06     462   709.6   500.9  699.74
   520.3   698.2   559.1   698.2   607.6  703.59   675.6  723.48   714.7  736.72
   724.5  738.58   831.4  738.36     926  741.56   954.4  739.68   992.3  743.94
#Mann= 3 , 0 , 0
       0      .1       0   520.3    .045       0   559.1      .1       0
Bank Sta=520.3,559.1
XS Rating Curve= 0 ,0
Exp/Cntr=0.3,0.1

Type RM Length L Ch R = 1 ,324.3   ,71.4,99.8,128.5
XS GIS Cut Line= 6
     1856152.394      412442.173     1856391.977      412314.569
     1856498.748      412220.819     1856678.436      412043.736
     1856759.165       411921.34     1856938.852      411913.527
#Sta/Elev= 30
       0  767.05    29.1  766.12    48.5  770.96    67.9  771.87      97  769.36
     126   759.1   174.5  752.79   184.2  749.78   193.9  744.84   232.7  719.17
   242.4   714.8   261.8  711.61   309.3  710.59   318.8  708.95   347.2  699.49
   366.2  697.28   375.6   697.1   404.3  697.11   423.2  698.62     462  711.96
   510.6  715.61   539.7  726.57   588.2     750   607.6  755.15     627  757.46
   812.4  749.55   840.8  750.22   935.5  737.37   973.4  735.14   992.3  736.36
#Mann= 3 , 0 , 0
       0      .1       0   366.2    .045       0   404.3      .1       0
Bank Sta=366.2,404.3
XS Rating Curve= 0 ,0
Exp/Cntr=0.3,0.1

Type RM Length L Ch R = 1 ,224.5   ,225.6,224.5,223.4
XS GIS Cut Line= 5
     1856162.811      412460.402     1856363.331      412369.256
     1856423.678      412315.761     1856880.626      412461.614
     1856972.387      412490.921
#Sta/Elev= 30
       0  752.46    28.7  749.84    47.9   751.2    76.6  748.16   153.2  728.95
   172.4  722.36   191.5  713.62   210.7  711.32     274  711.03     292  709.71
   300.9  707.63   320.5  698.31   340.1   697.1   369.4  697.45   379.2  699.79
   398.8  710.37   408.6  712.28   428.2  713.48   467.3  713.46   565.2  708.68
   614.2  716.31   643.5  715.72   663.1  713.06   672.9   714.1   692.5  725.51
   731.6   742.7     761   749.9   780.6  757.79   838.4  776.96   876.9  793.67
#Mann= 3 , 0 , 0
       0      .1       0   320.5    .045       0   369.4      .1       0
#XS Ineff= 2 , 0
                          502.21           742.3
Permanent Ineff=
       F       F
Bank Sta=320.5,369.4
XS Rating Curve= 0 ,0
Exp/Cntr=0.3,0.1

Chan Stop Cuts=-1
Use User Specified Reach Order=0
Composite Channel Slope=5